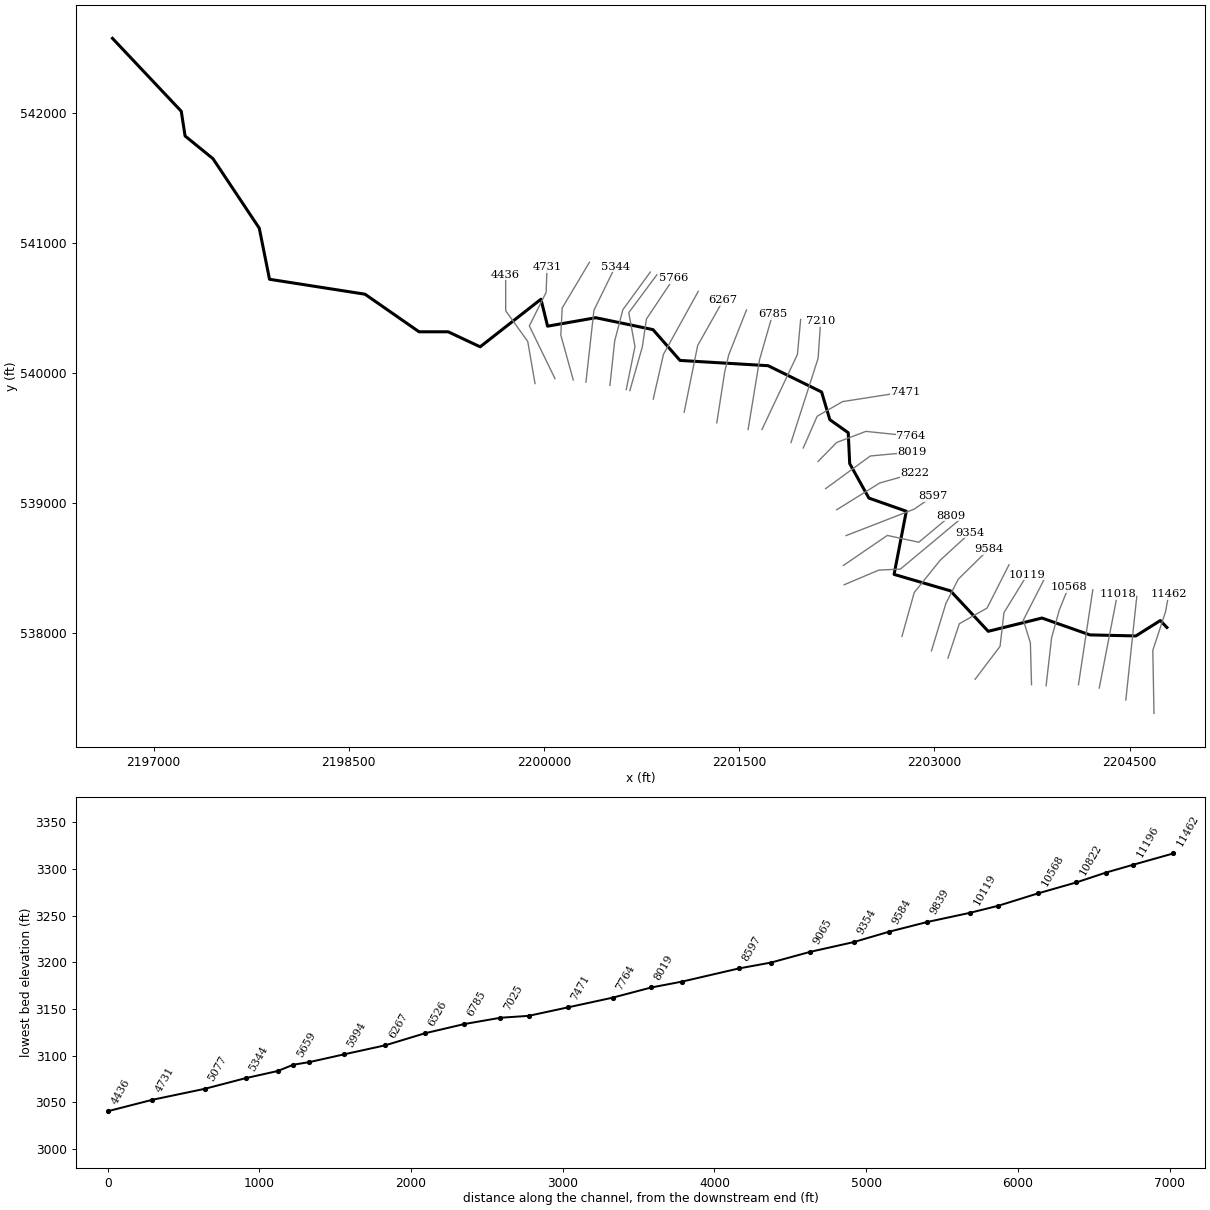
--- BERGOOCK.prj (project) ---

Proj Title=BERGOOCK
Current Plan=p01
Default Exp/Contr=0,0
English Units
Geom File=g01
Flow File=f01
Plan File=p01
BEGIN DESCRIPTION:
----------MODEL BY WOOD PLC 2022----------
AFH study
Randolph County, WV
HEC-RAS Version: RAS 6.2
Vertical Datum: NAVD88
Projection: NAD 1983 StatePlane West Virginia S FIPS 4702 (US Feet)
Terrain: 1-meter LIDAR (FEMA Region III 3DEP collected 2016-2018)
Land Use: 2019 NLCD
Hydrologic Method:
WV SIR2010-5033 regression equations
Additional Model Notes:
Stream begins outside of county boundary;
END DESCRIPTION:
DSS Export Rating Curves= 0
DSS Export Rating Curve Sorted= 0
DSS Export Volume Flow Curves= 0
DXF OffsetX= 0
DXF OffsetY= 0
DXF ScaleX= 0
DXF ScaleY= 0

--- BERGOOCK.p01 (plan) ---

Plan Title=Floodplain
Program Version=6.20
Short Identifier=Floodplain
Geom File=g01
Flow File=f01
Subcritical Flow
K Sum by GR= 0
Std Step Tol= 0.01
Critical Tol= 0.01
Num of Std Step Trials= 20
Max Error Tol= 0.3
Flow Tol Ratio= 0.001
Split Flow NTrial= 30
Split Flow Tol= 0.02
Split Flow Ratio= 0.02
Log Output Level= 0
Friction Slope Method= 1
Unsteady Friction Slope Method= 2
Unsteady Bridges Friction Slope Method= 1
Parabolic Critical Depth
Global Vel Dist= 0 , 0 , 0
Global Log Level= 0
CheckData=True
Encroach Param=-1 ,0,0, 0
Mapping Interval=1HOUR
Computation Time Step Use Courant=        0
Computation Time Step Use Time Series=    0
Computation Time Step Count To Double=0
Computation Time Step Max Doubling=0
Computation Time Step Max Halving=0
Computation Time Step Residence Courant=0
Run HTab= 0
Run UNet= 0
Run Sediment= 0
Run PostProcess= 0
Run WQNet= 0
Run RASMapper=-1
UNET Theta= 0
UNET Theta Warmup= 0
UNET ZTol= 0
UNET ZSATol= 0
UNET MxIter= 0
UNET Max Iter WO Improvement= 0
UNET MaxInSteps= 0
UNET DtIC= 0
UNET DtMin= 0
UNET MaxCRTS= 0
UNET WFStab= 0
UNET SFStab= 0
UNET WFX= 1
UNET SFX= 1
UNET Gravity=32.174
UNET 1D Methodology=Finite Difference
UNET DSS MLevel= 1
UNET Pardiso=0
UNET DZMax Abort= 0
UNET Use Existing IB Tables= 0
UNET Froude Reduction=False
UNET Froude Limit= 0
UNET Froude Power= 0
UNET D1 Cores= 0
UNET WindReference=Eulerian
UNET WindDragFormulation=Hsu (1988)
UNET D2 Coriolis=0
UNET D2 Cores= 0
UNET D2 Theta= 1
UNET D2 Theta Warmup= 1
UNET D2 Z Tol= 0.01
UNET D2 Volume Tol= 0.01
UNET D2 Max Iterations= 20
UNET D2 Equation= 0
UNET D2 RampUpFraction=0.1
UNET D2 TimeSlices= 1
UNET D2 Turbulence Formulation=Non-Conservative (original)
UNET D2 Eddy Viscosity=0.3
UNET D2 Transverse Eddy Viscosity=0.1
UNET D2 Smagorinsky Mixing=0
UNET D2 BCVolumeCheck=0
UNET D2 Cores=0
UNET D2 SolverType=PARDISO (Direct)
UNET D2 Minimum Iterations= 2147483647
UNET D2 Maximum Iterations= 2147483647
UNET D2 Restart Number= 10
UNET D2 Relaxation Coeff=1.3
UNET D2 SOR Precondition Iterations= 10
UNET D2 ILUT Maximum Fill= 8
UNET D2 ILUT Tolerance=1E-08
UNET D1D2 MaxIter= 0
UNET D1D2 ZTol=0.01
UNET D1D2 QTol=0.1
UNET D1D2 MinQTol=1
Write IC File= 0
Write IC File at Fixed DateTime=0
Write IC File at Sim End=0
Echo Input=False
Echo Parameters=False
Echo Output=False
Write Detailed= 0
HDF Write Warmup=0
HDF Write Time Slices=0
HDF Flush=0
HDF Compression= 1
HDF Chunk Size= 1
HDF Spatial Parts= 1
HDF Use Max Rows=0
HDF Fixed Rows= 1
Calibration Method= 0
Calibration Iterations= 20
Calibration Max Change=0.05
Calibration Tolerance=0.2
Calibration Maximum=1.5
Calibration Minimum=0.5
Calibration Optimization Method= 1
WQ AD Non Conservative
WQ ULTIMATE=-1
WQ Max Comp Step=1HOUR
WQ Output Interval=15MIN
WQ Output Selected Increments= 0
WQ Output face flow=0
WQ Output face velocity=0
WQ Output face area=0
WQ Output face dispersion=0
WQ Output cell volume=0
WQ Output cell surface area=0
WQ Output cell continuity=0
WQ Output cumulative cell continuity=0
WQ Output face conc=0
WQ Output face dconc_dx=0
WQ Output face courant=0
WQ Output face peclet=0
WQ Output face adv mass=0
WQ Output face disp mass=0
WQ Output cell mass=0
WQ Output cell source sink temp=0
WQ Output nsm pathways=0
WQ Output nsm derived pathways=0
WQ Create Restart=0
WQ Fixed Restart=0
WQ System Summary=0
WQ Write To DSS=0
Sorting and Armoring Iterations= 10
XS Update Threshold= 0.02
Bed Roughness Predictor= 0
Hydraulics Update Threshold= 0.02
Energy Slope Method= 1
Volume Change Method= 1
Sediment Retention Method= 0
Sediment TS Multiplier= 1
Warm Up Method= 0
XS Weighting Method= 0
Number of US Weighted Cross Sections= 1
Number of DS Weighted Cross Sections= 1
Upstream XS Weight=0
Main XS Weight=1
Downstream XS Weight=0
Number of DS XS's Weighted with US Boundary= 1
Upstream Boundary Weight= 1
Weight of XSs Associated with US Boundary= 0
Number of US XS's Weighted with DS Boundary= 1
Downstream Boundary Weight= 0.5
Weight of XSs Associated with DS Boundary= 0.5
Percentile Method= 0
Sediment Output Level= 3
Mass or Volume Output= 0
Output Increment Type= 1
Profile and TS Output Increment= 1
Transport Output Increment 1
XS Output Flag= 0
XS Output Increment= 10
Read HDF5 Sediment Hotstart= 0
Sediment Hotstart Type= 0
Write Gradation File= 0
Read Gradation Hotstart= 0
Write HDF5 File= 1
Write Binary Output= 1
Write DSS Sediment File= 0
DSS Sediment Output Type= 1
SV Curve= 0
Specific Gage Flag= 0
Subcell Erosion Methods= 0
Subcell Deposition Methods= 0
Advection Scheme= 1
Matrix Solver= 0
Implicit Weighting Factor= 1
Maximum Outer Loop Convergence Iterations= 5
Convergence Maximum Absolute= 0.001
Convergence RMSE= 0.0001
Grain Fractions Max Abs Error= 0.001
Max Subgrid Regions= 1
Max Subgrid Length Scale= 3.402823E+38
Initial Layer Thickness= 3.402823E+38
Min Layer Thickness= 3.402823E+38
Max Layer Thickness= 3.402823E+38
Number of Layers= 5

--- BERGOOCK.f01 (steady flow) ---

Flow Title=Flow
Program Version=6.20
Number of Profiles= 1
Profile Names=P100yr
River Rch & RM=BERGOOCK,Main,11462
     392
River Rch & RM=BERGOOCK,Main,9065
     461
River Rch & RM=BERGOOCK,Main,7471
     636
River Rch & RM=BERGOOCK,Main,5994
     711
River Rch & RM=BERGOOCK,Main,3957
     858
River Rch & RM=BERGOOCK,Main,330
     980
Boundary for River Rch & Prof#=BERGOOCK,Main            , 1
Up Type= 0
Dn Type= 3
Dn Slope=0.0397
DSS Import GetInterval= 0
DSS Import GetPeak= 0
DSS Import FillOption= 0

--- BERGOOCK.g01 (geometry) ---

Geom Title=Geometry
Program Version=6.20

River Reach=BERGOOCK        ,Main
Reach XY= 30
     2204786.679      538041.977     2204736.158      538095.102
 2204548.0854808537976.794317192     2204195.012      537984.685
     2203826.783      538114.373     2203413.762       538012.29
     2203124.179      538323.227     2202690.159      538449.974
     2202784.075      538935.727     2202496.575      539036.768
     2202349.179      539301.8732202337.85821932539539.199872886
     2202196.575      539639.6332202133.08718281539852.641085936
     2201722.318      540054.728     2201044.972      540095.248
     2200837.554      540332.082     2200398.087      540423.736
     2200027.498      540358.632     2199976.508       540565.98
     2199509.298      540199.853  2199263.405156540315.439358007
2199039.82551401540315.498780007     2198624.265      540604.521
     2197890.535      540719.375     2197811.948      541112.011
     2197456.218      541646.526     2197241.728      541821.201
2197212.44745451542011.060014527     2196683.798      542571.984

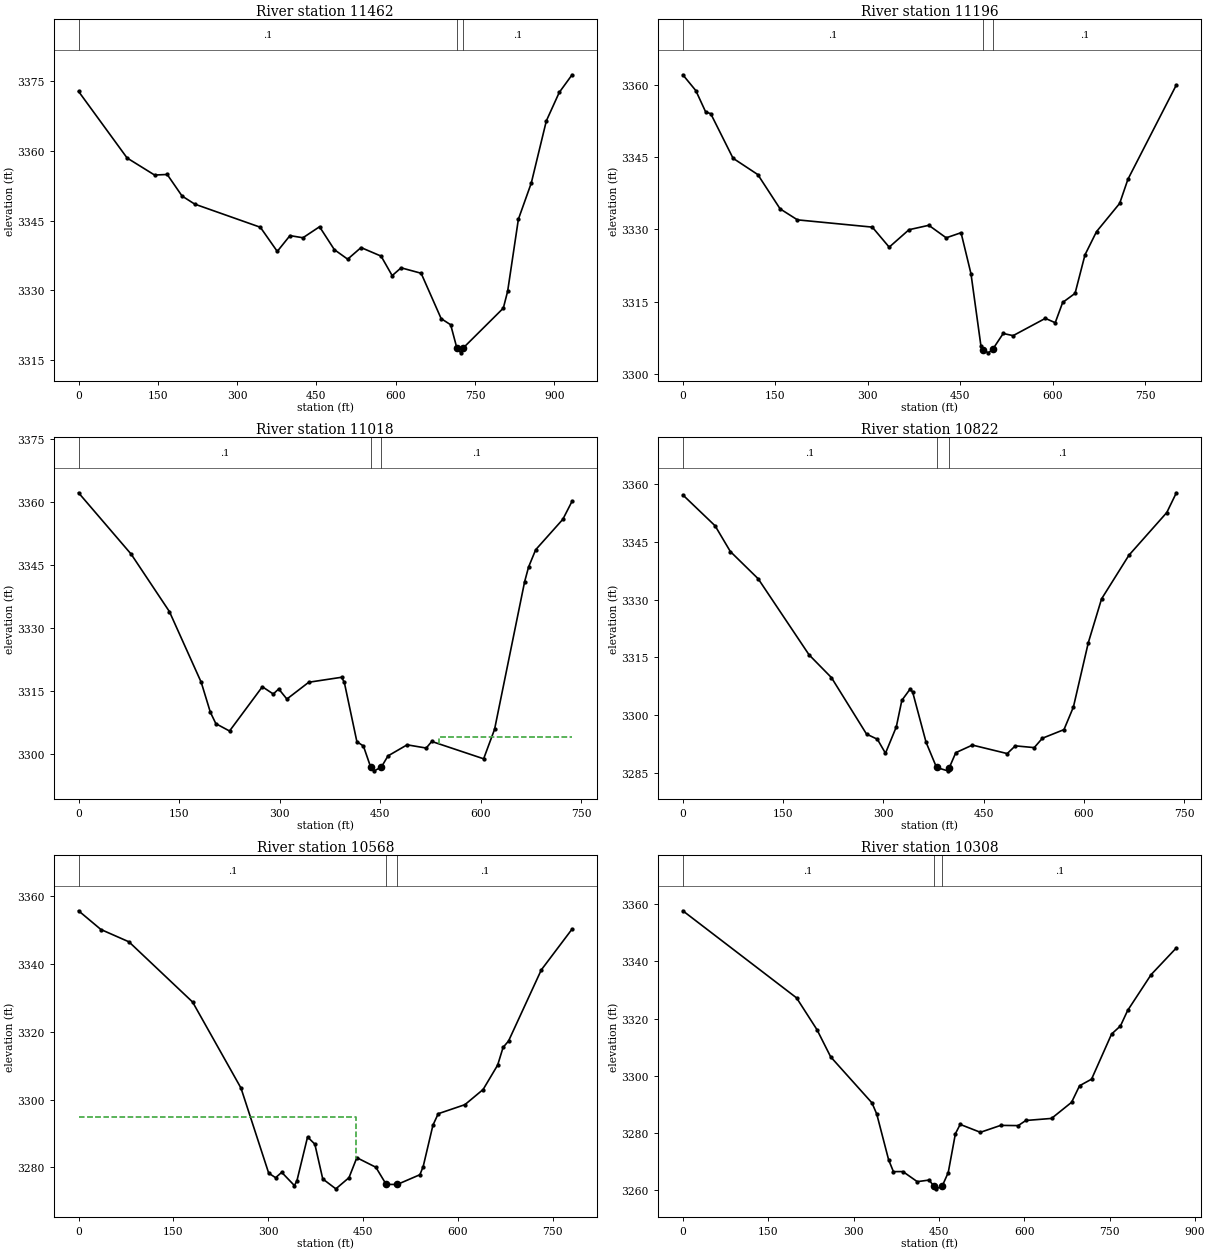
Type RM Length L Ch R = 1 ,11462   ,266,266,266
XS GIS Cut Line= 4
2204687.46757767537381.2817660152204678.45285724537865.793817326
2204776.16271684538162.7573175532204800.79975794538297.082315146
#Sta/Elev= 30
       0 3372.84    91.9  3358.5   143.9 3354.83   167.8 3354.95   195.9 3350.31
   219.9 3348.57     344 3343.59     376 3338.39     400 3341.79   424.6 3341.33
     456  3343.7     484 3338.77   509.2 3336.72   534.5 3339.22   572.4 3337.38
   593.4 3333.18   610.3 3334.86   648.2 3333.69   686.1 3323.92   704.1  3322.6
   715.6 3317.68   723.1 3316.56   728.2 3317.65   803.7 3326.18   811.9 3329.83
   832.2 3345.32   856.6 3353.11   885.1 3366.49   909.5 3372.61   933.8 3376.41
#Mann= 3, -1 ,  0
       0     0.1       0   715.6   0.045       0   728.2     0.1       0
Bank Sta=715.6,728.2
XS Rating Curve= 0 ,0
Exp/Cntr=0.3,0.1

Type RM Length L Ch R = 1 ,11196   ,177.8,177.8,177.8
XS GIS Cut Line= 2
2204471.10386292537484.1721699032204555.12331988538280.606605704
#Sta/Elev= 30
       0 3362.11    21.1 3358.83    37.2 3354.36    45.3 3354.04    81.5 3344.78
   121.7 3341.39   157.9 3334.27     186 3331.99   307.5 3330.48   334.9 3326.32
     367 3329.94   399.2 3330.86   427.4 3328.26   451.5 3329.32   467.6 3320.81
   483.7 3305.87  486.57 3305.07   495.7 3304.38  502.72 3305.08   519.9  3308.4
     536 3307.95   588.3 3311.54   604.3 3310.63   616.4 3314.84   636.5 3316.73
   652.6 3324.72   671.3 3329.54   708.9 3335.41   722.3 3340.42   800.9 3360.01
#Mann= 3, -1 ,  0
       0     0.1       0  486.57   0.045       0  502.72     0.1       0
Bank Sta=486.57,502.72
XS Rating Curve= 0 ,0
Exp/Cntr(USF)=0,0
Exp/Cntr=0.3,0.1

Type RM Length L Ch R = 1 ,11018   ,195.9,195.9,195.9
XS GIS Cut Line= 2
2204266.75780878537576.1101338352204406.70283747538298.663302133
#Sta/Elev= 30
       0 3362.12    78.5 3347.54   135.5 3333.91     183 3317.09   196.6 3309.99
   204.8 3307.28   225.2 3305.54   274.1 3316.05   290.4 3314.33   298.5 3315.53
   310.7 3313.13   343.3 3317.12   392.2  3318.3   396.3 3317.13   415.1    3303
   424.8 3301.98   435.6 3296.99   441.1 3296.08  451.59 3296.99   461.5 3299.63
     490 3302.26   518.5 3301.49   526.7 3303.06   604.1 3298.94   620.4 3305.94
   665.2 3340.98   671.1 3344.48   681.7 3348.59   722.2 3355.82     736 3360.12
#Mann= 3, -1 ,  0
       0     0.1       0   435.6   0.045       0  451.59     0.1       0
#XS Ineff= 2 , 0
                          537.68         3304.18
Permanent Ineff=
       F       F
Bank Sta=435.6,451.59
XS Rating Curve= 0 ,0
Exp/Cntr=0.3,0.1

Type RM Length L Ch R = 1 ,10822   ,254.6,254.6,254.6
XS GIS Cut Line= 2
2204107.01954941537601.4493285822204217.29508667538331.368360953
#Sta/Elev= 30
       0 3357.27    48.3 3349.23    71.1 3342.54   112.7 3335.46   188.9 3315.66
   222.3 3309.75   274.8 3295.06     291 3293.72   303.1 3290.07   319.3 3296.92
   327.6 3303.83   339.5 3306.66   343.6 3306.09   363.8 3292.95   379.5 3286.38
   396.2  3285.5   398.6 3286.34   408.3 3290.23   433.1  3292.2   485.2 3289.99
   497.3    3292   525.6 3291.54   537.8 3293.98   570.1 3296.22   584.2  3302.1
   606.5 3318.84   626.3 3330.22   667.2 3341.57   723.9 3352.69   738.2 3357.82
#Mann= 3, -1 ,  0
       0     0.1       0   379.5   0.045       0   398.6     0.1       0
Bank Sta=379.5,398.6
XS Rating Curve= 0 ,0
Exp/Cntr(USF)=0,0
Exp/Cntr=0.3,0.1

Type RM Length L Ch R = 1 ,10568   ,259.2,259.2,259.2
XS GIS Cut Line= 4
2203858.48759465537593.9813785862203900.47171771537962.032831384
2203960.00802484 538176.497835552204030.17375717538350.402086073
#Sta/Elev= 30
       0 3355.63    35.4 3350.11    79.7 3346.48   180.4 3328.73   256.9 3303.37
   300.7 3278.31   311.6 3276.95   321.3 3278.54   341.4 3274.63   345.4 3276.08
   362.2 3288.97   373.7 3286.84   386.2 3276.59   406.9 3273.67   427.7 3276.96
   440.1 3282.85   470.2 3280.03   486.5 3274.99   503.9 3274.95   539.8 3277.83
     545 3280.22   560.5 3292.46   568.8 3295.81     611 3298.48   639.8 3302.95
   662.8 3310.15   671.4 3315.37     680 3317.24   731.8  3338.2   780.5 3350.24
#Mann= 3, -1 ,  0
       0     0.1       0   486.5   0.045       0   503.9     0.1       0
#XS Ineff= 2 , 0
          438.99 3294.91
Permanent Ineff=
       F       F
Bank Sta=486.5,503.9
XS Rating Curve= 0 ,0
Exp/Cntr=0.3,0.1

Type RM Length L Ch R = 1 ,10308   ,189.4,189.4,189.4
XS GIS Cut Line= 4
2203746.43604661537601.4493285822203737.68401984537923.523913609
2203683.42145389538098.5644489492203847.95955711538420.639033976
#Sta/Elev= 30
       0 3357.67   199.8 3327.25   235.7 3316.13   259.8 3306.63   332.3 3290.56
   340.7 3286.66   361.6 3270.65     370 3266.54   386.7 3266.56   411.9 3263.04
   432.8  3263.6  440.61 3261.56   445.4 3260.53   455.8 3261.52   466.3 3266.22
   478.9 3279.79   487.3 3283.04   522.8 3280.28   558.5  3282.7   589.2 3282.62
   602.7 3284.41   647.8 3285.13     683 3290.76     697 3296.54   718.1 3298.85
   753.3 3314.61   768.9 3317.45   781.5 3322.85   822.8 3335.38   867.1 3344.71
#Mann= 3, -1 ,  0
       0     0.1       0  440.61   0.045       0   455.8     0.1       0
Bank Sta=440.61,455.8
XS Rating Curve= 0 ,0
Exp/Cntr(USF)=0,0
Exp/Cntr=0.3,0.1

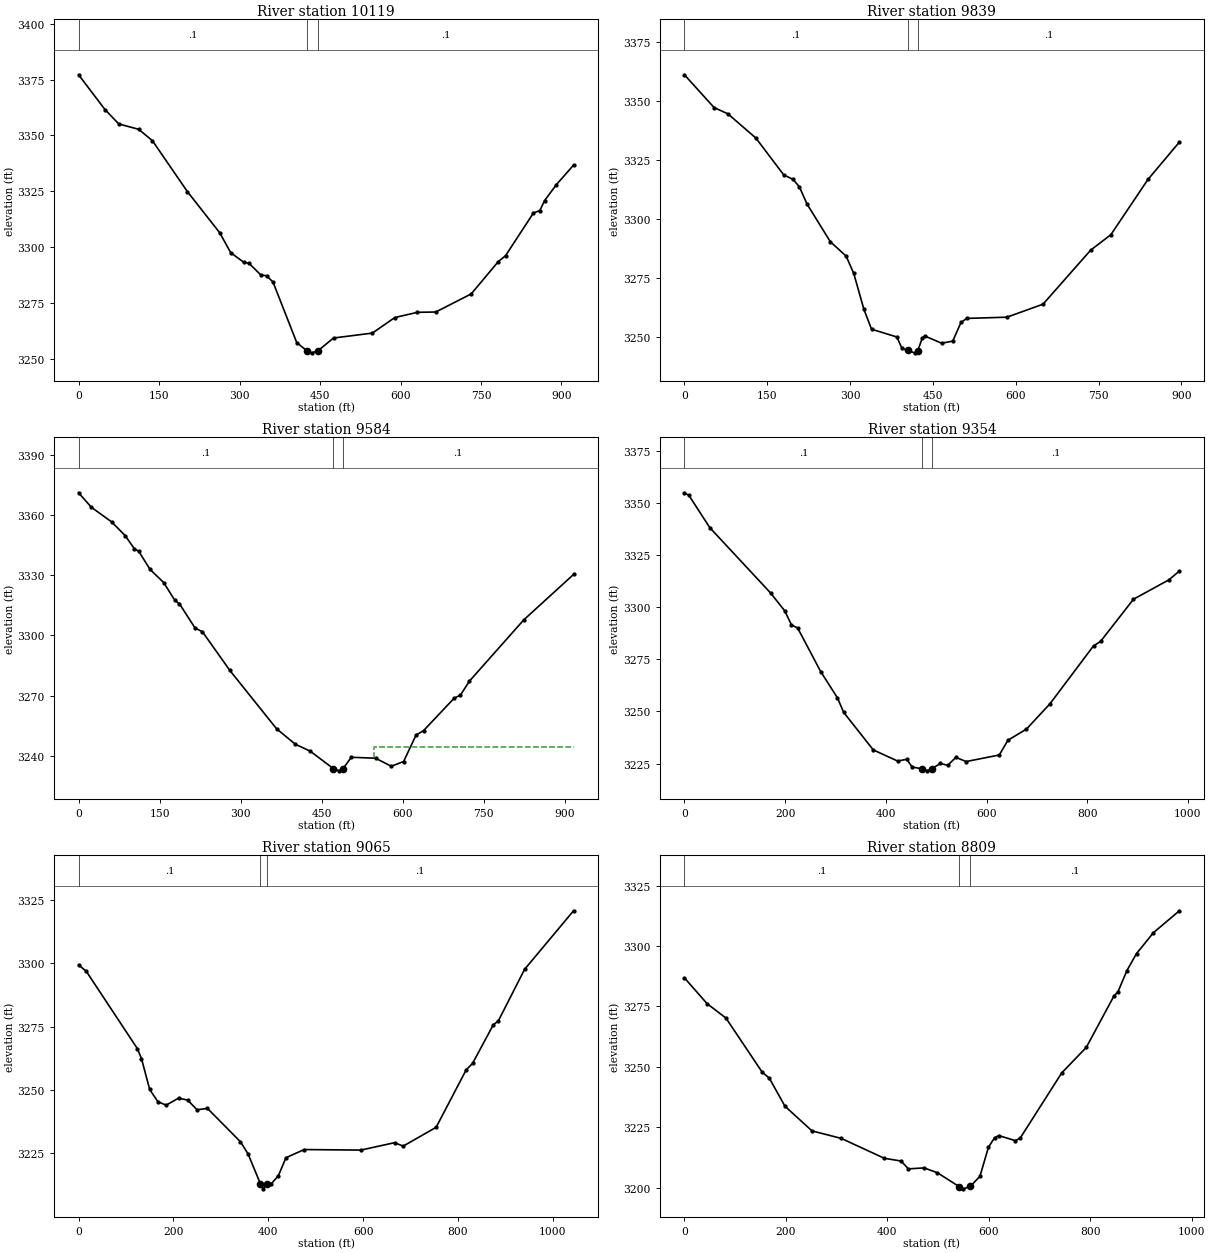
Type RM Length L Ch R = 1 ,10119   ,279.7,279.7,279.7
XS GIS Cut Line= 4
2203312.88281263 537643.559403432203504.51526767537896.560246675
2203534.63699885538156.3278256122203714.98118545538448.835921623
#Sta/Elev= 30
       0 3377.12    49.2 3361.57    74.9 3355.15     112 3352.75   137.5 3347.69
   202.7 3324.93     263 3306.52   283.7 3297.55   308.1 3293.29   317.4 3292.91
   339.3 3287.74   350.4 3287.26   362.3 3284.52   406.6 3257.42   425.9 3253.68
   434.8 3252.85     446 3253.75   475.1 3259.48   547.5 3261.67   589.4 3268.63
   631.6 3270.96   665.7  3271.1   731.8 3279.19     782 3293.57   795.7 3296.26
   847.7 3315.34   859.7 3316.44   868.4 3320.84     890 3327.87   922.5 3336.75
#Mann= 3, -1 ,  0
       0     0.1       0   425.9   0.045       0     446     0.1       0
Bank Sta=425.9,446
XS Rating Curve= 0 ,0
Exp/Cntr=0.3,0.1

Type RM Length L Ch R = 1 ,9839    ,255.8,255.8,255.8
XS GIS Cut Line= 4
2203104.03728191 537806.246754932203191.55754958538070.557963295
2203405.10700269 538191.335932682203573.14591662538523.912949828
#Sta/Elev= 30
       0 3361.28    53.7 3347.36    78.9 3344.66   129.5 3334.37   179.7 3318.79
   196.9 3316.78   208.2 3313.67   222.2 3306.29   264.3 3290.32   292.9 3284.22
   306.7 3276.84   325.1 3261.59   338.9 3253.15   384.8 3249.85     394    3245
   404.1 3244.12     417 3243.11  422.76  3244.1   430.8 3249.41   435.4 3250.26
   465.7 3247.21   485.9 3248.08   500.9 3256.02   511.3 3257.74   584.1 3258.26
   649.5 3263.79   735.8 3286.76   772.3  3293.3   839.5 3316.79   896.4 3332.66
#Mann= 3, -1 ,  0
       0     0.1       0   404.1   0.045       0  422.76     0.1       0
Bank Sta=404.1,422.76
XS Rating Curve= 0 ,0
Exp/Cntr(USF)=0,0
Exp/Cntr=0.3,0.1

Type RM Length L Ch R = 1 ,9584    ,229.7,229.7,229.7
XS GIS Cut Line= 4
2202977.28637474537862.6065698032203088.28363373538226.344039748
2203183.00653726 538412.563619492203415.84864626 538641.86694839
#Sta/Elev= 30
       0 3371.05    23.6 3363.84    61.2 3356.52    86.3 3349.68   103.1 3343.19
   111.4 3341.84   132.3 3332.85   157.4 3326.34   178.3 3317.38   186.7 3315.73
   215.5 3303.65   229.2 3301.81   279.9 3282.53   366.5 3253.43   401.4 3245.69
   428.4 3242.36   471.6 3233.58   482.2  3232.5   489.4 3233.59   504.6 3239.26
   549.5 3238.79   578.7 3234.79   601.5 3237.15   624.4 3250.26   638.6 3252.59
   695.1 3268.71   706.5 3270.18   723.4 3277.24   823.8  3307.7     916 3330.35
#Mann= 3, -1 ,  0
       0     0.1       0   471.6   0.045       0   489.4     0.1       0
#XS Ineff= 2 , 0
                          546.68         3244.36
Permanent Ineff=
       F       F
Bank Sta=471.6,489.4
XS Rating Curve= 0 ,0
Exp/Cntr=0.3,0.1

Type RM Length L Ch R = 1 ,9354    ,288.5,288.5,288.5
XS GIS Cut Line= 4
2202750.45540052537972.535263504 2202844.9772896538310.363496712
2203044.52349989538558.9210568962203275.57700654538770.720104658
#Sta/Elev= 30
       0 3354.83       9 3353.57    50.5 3338.09     171 3306.84   199.4 3298.19
   212.5 3291.56     225 3289.97   270.7 3269.11   303.9 3256.55   316.3 3249.58
   375.1 3231.58   423.4 3226.25   441.6 3227.08   452.4 3223.36   472.4 3222.52
   482.7 3221.55   490.8  3222.5   508.3 3225.07     523  3224.2   539.1 3228.01
   559.6    3226   625.4 3229.15   642.5 3236.21   679.4 3241.58   726.2 3253.74
   812.5 3281.45   826.4 3283.56   891.9 3303.81   962.1 3313.08     983 3317.29
#Mann= 3, -1 ,  0
       0     0.1       0   472.4   0.045       0   490.8     0.1       0
Bank Sta=472.4,490.8
XS Rating Curve= 0 ,0
Exp/Cntr(USF)=0,0
Exp/Cntr=0.3,0.1

Type RM Length L Ch R = 1 ,9065    ,256.5,256.5,256.5
XS GIS Cut Line= 4
2202306.11942099538370.0325677922202573.40650873 538483.24184296
2202738.42535151538490.5470409892203190.05474211538867.273073485
#Sta/Elev= 30
       0 3299.44    16.2  3296.9   123.9 3266.39   132.6 3262.44   149.9 3250.25
   167.3 3245.39   184.7 3244.08   210.7 3246.83   229.8 3246.08   249.8 3242.24
   271.6 3242.79   341.1 3229.65   357.1 3224.91  383.27 3213.06   389.1 3211.03
   397.1  3213.1   405.2 3212.81   421.2  3216.2   437.2 3223.31   475.6 3226.54
   594.9 3226.32   666.1 3229.25   684.4 3227.89   753.9 3235.33   817.1 3257.96
   830.6 3260.53   874.4 3275.78   884.9  3277.3   940.4 3297.69  1043.6  3320.8
#Mann= 3, -1 ,  0
       0     0.1       0  383.27   0.045       0   397.1     0.1       0
Bank Sta=383.27,397.1
XS Rating Curve= 0 ,0
Exp/Cntr=0.3,0.1

Type RM Length L Ch R = 1 ,8809    ,212.3,212.3,212.3
XS GIS Cut Line= 4
2202300.60122469538518.661733767 2202638.4294579538749.715240417
2202879.98539667538697.2030798152203125.04214615538902.000506164
#Sta/Elev= 30
       0 3286.84    44.7 3276.18    81.9 3270.21   153.3 3247.86   167.4 3245.37
   198.2 3233.78   251.5 3223.58   309.4 3220.46   394.2 3212.24   427.4 3211.11
   441.5 3207.88   472.5 3208.27   498.6 3206.29   541.6 3200.56   550.2 3199.62
  563.66 3200.64   582.7 3204.83   599.4 3216.82   611.6 3220.78   619.8 3221.64
   652.6 3219.53   662.3 3220.69   743.8 3247.52   792.3 3258.09   846.9 3279.37
   854.8 3281.11   872.4 3289.85   891.3 3296.87   924.7 3305.51   975.8 3314.57
#Mann= 3, -1 ,  0
       0     0.1       0   541.6   0.045       0  563.66     0.1       0
Bank Sta=541.6,563.66
XS Rating Curve= 0 ,0
Exp/Cntr(USF)=0,0
Exp/Cntr=0.3,0.1

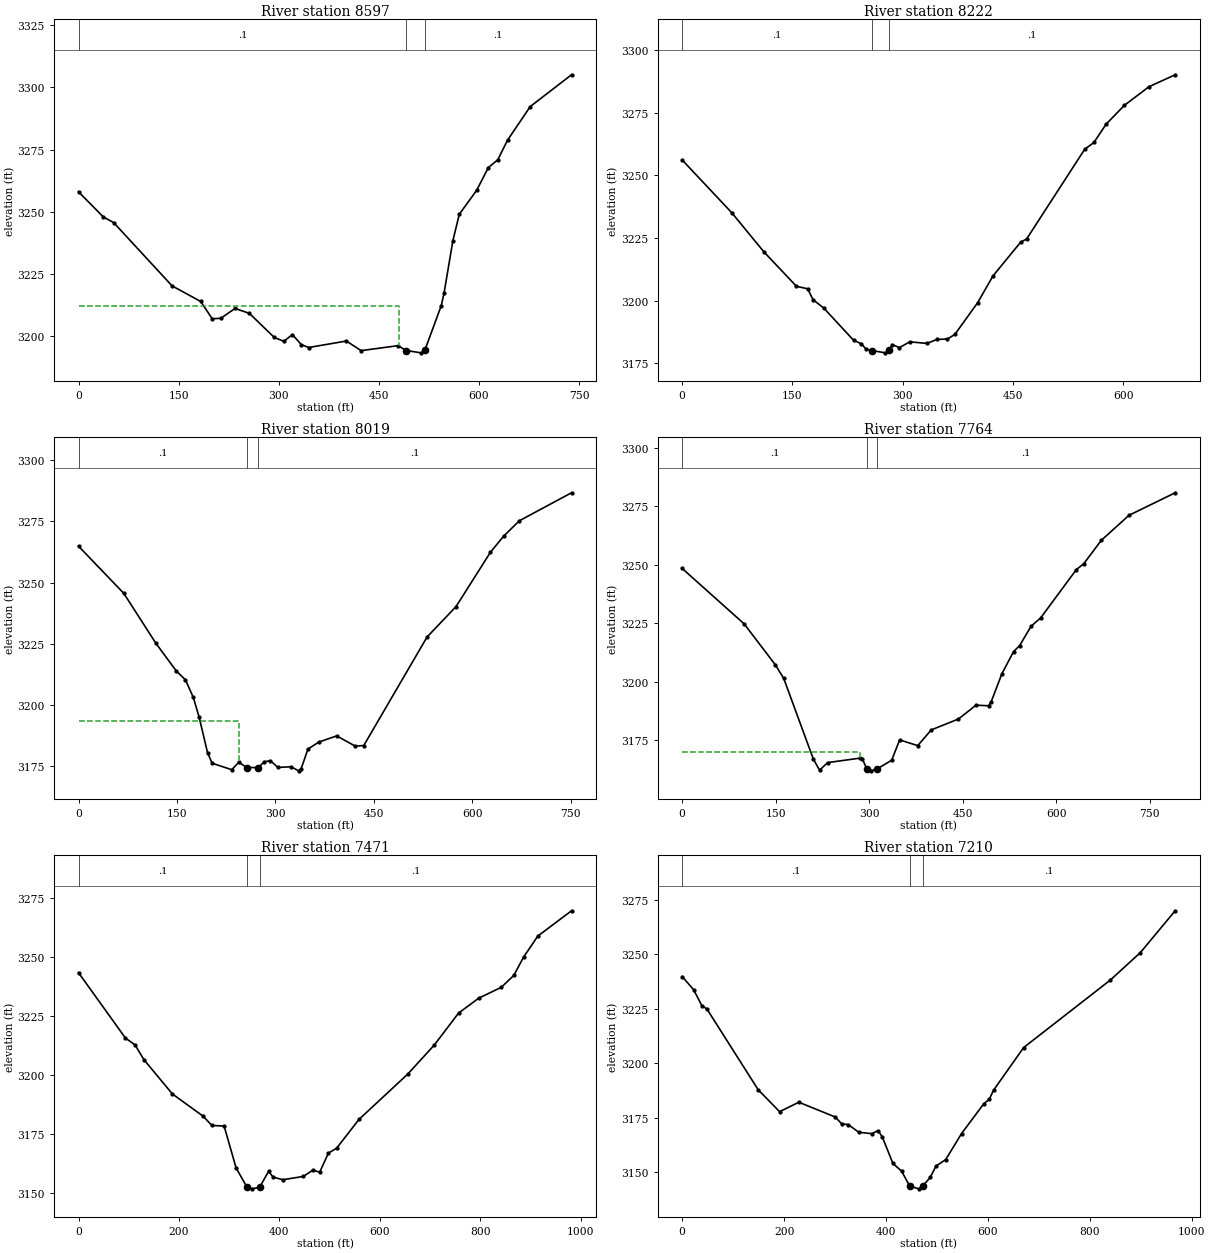
Type RM Length L Ch R = 1 ,8597    ,374.1,374.1,374.1
XS GIS Cut Line= 3
2202321.42146855538748.4809617872202842.35423692538950.589231629
2202991.31273016539051.562079368
#Sta/Elev= 30
       0 3258.02    37.3 3247.89    52.7 3245.64   140.2 3220.22   183.2 3213.94
   200.3 3207.01   213.2 3207.19   234.6 3211.14     256 3209.18   293.2 3199.53
   307.6 3197.95   320.5 3200.64   333.7 3196.65   344.8 3195.45   401.4 3198.06
   423.4  3194.2   478.7 3196.19   491.1 3194.24   513.5 3193.31   518.9 3194.32
   543.6 3212.32   547.8 3217.43     561 3238.45   570.6 3249.02   596.5 3258.57
   614.1 3267.75   628.2 3270.88   643.1 3278.87   676.9 3292.28   738.7 3305.04
#Mann= 3, -1 ,  0
       0     0.1       0   491.1   0.045       0   518.9     0.1       0
#XS Ineff= 2 , 0
          480.27 3212.19
Permanent Ineff=
       F       F
Bank Sta=491.1,518.9
XS Rating Curve= 0 ,0
Exp/Cntr=0.3,0.1

Type RM Length L Ch R = 1 ,8222    ,203.8,203.8,203.8
XS GIS Cut Line= 3
2202249.39137688538947.0522860942202579.74537923539152.637394852
2202850.55059145 539229.20012501
#Sta/Elev= 30
       0 3256.16    67.5 3235.09     111 3219.55   155.4 3205.77   170.6 3204.77
   178.1 3200.37   192.3 3197.16     233 3184.27   243.6 3182.85   250.4  3180.6
   257.7 3180.15   276.5 3179.22   281.2 3180.21     286  3182.5   295.4  3181.3
   309.5 3183.61   333.1 3182.98   346.2 3184.55   360.8 3184.75   370.8 3186.55
     402 3199.29   422.8 3209.94   460.2 3223.32   468.5 3224.67   547.5 3260.45
     560 3263.14   576.6 3270.45   601.5 3277.97   634.8 3285.37   670.5 3290.14
#Mann= 3, -1 ,  0
       0     0.1       0   257.7   0.045       0   281.2     0.1       0
Bank Sta=257.7,281.2
XS Rating Curve= 0 ,0
Exp/Cntr(USF)=0,0
Exp/Cntr=0.3,0.1

Type RM Length L Ch R = 1 ,8019    ,254.6,254.6,254.6
XS GIS Cut Line= 3
2202163.81114697539109.1114385642202507.55520694539360.478670193
2202831.21348501539390.581441506
#Sta/Elev= 30
       0 3264.89      69 3245.56   117.7  3225.2   149.1 3213.72   162.8  3210.2
   174.9 3202.94   183.8 3194.79   196.6 3180.26   203.6 3176.02   233.4 3173.38
   244.1 3176.39  256.44 3174.27  273.94 3174.25   282.9 3176.62   292.3 3177.05
   303.7  3174.3   323.7 3174.58   335.2 3172.91   338.9 3173.62   349.5 3181.82
     366 3184.68   393.2 3187.22   421.7    3183   434.5 3183.28   530.9  3227.7
   575.1 3240.18   627.3 3262.34   647.4 3268.95   671.5 3275.29   750.9 3286.74
#Mann= 3, -1 ,  0
       0     0.1       0  256.44   0.045       0  273.94     0.1       0
#XS Ineff= 2 , 0
          244.66 3193.42
Permanent Ineff=
       F       F
Bank Sta=256.44,273.94
XS Rating Curve= 0 ,0
Exp/Cntr=0.3,0.1

Type RM Length L Ch R = 1 ,7764    ,292.8,292.8,292.8
XS GIS Cut Line= 4
2202106.19071491539318.5233101942202249.39137688539464.559628829
2202473.40825401539549.6293290042202817.94053972539514.183620598
#Sta/Elev= 30
       0 3248.39    99.5 3224.69   149.4 3207.24   162.8 3201.45   210.3 3167.01
   220.3 3162.25   233.2  3165.5   284.7 3167.39   288.8  3167.2  296.04 3162.72
   303.3 3161.98   311.7 3162.67   335.9  3166.5   348.7 3175.19   377.7 3172.74
   399.4 3179.46   442.9 3184.09   471.1 3190.02   491.2 3189.76   495.2 3191.27
   512.7 3203.48   531.4 3212.92   540.9 3215.38   559.5 3223.74   574.7 3227.24
   631.9 3247.86     644 3250.44   672.1 3260.42   716.4 3271.08   790.5  3280.7
#Mann= 3, -1 ,  0
       0     0.1       0  296.04   0.045       0   311.7     0.1       0
#XS Ineff= 2 , 0
           284.7    3170
Permanent Ineff=
       F       F
Bank Sta=296.04,311.7
XS Rating Curve= 0 ,0
Exp/Cntr(USF)=0,0
Exp/Cntr=0.3,0.1

Type RM Length L Ch R = 1 ,7471    ,261.3,261.3,261.3
XS GIS Cut Line= 4
 2201992.1234221539422.0208365672202099.10157323539665.891252577
2202293.70312522 539778.533751912202778.35502704539854.130269842
#Sta/Elev= 30
       0 3243.34    93.5 3215.59   112.6 3212.72   130.1 3206.49   186.9 3191.92
   248.1 3182.48   265.5 3178.56     290 3178.28   313.8 3160.54   335.6 3152.33
   345.6 3151.67  360.65 3152.32   378.5  3159.1   387.7 3156.62   407.1 3155.54
   447.8 3156.93   466.3 3159.56   480.3 3158.77   497.7 3166.85   513.9 3168.87
   558.4 3181.09   655.6 3200.33   708.2 3212.59   756.8 3226.19   796.8  3232.5
   841.8 3237.12   866.9 3242.19   886.3 3249.96   914.7 3258.87   981.7 3269.58
#Mann= 3, -1 ,  0
       0     0.1       0   335.6   0.045       0  360.65     0.1       0
Bank Sta=335.6,360.65
XS Rating Curve= 0 ,0
Exp/Cntr=0.3,0.1

Type RM Length L Ch R = 1 ,7210    ,184.9,184.9,184.9
XS GIS Cut Line= 3
2201897.76994948539463.1418004932202106.19071491540111.089350163
2202126.04031162540397.490674088
#Sta/Elev= 30
       0 3239.77    22.6 3233.69    38.5 3226.48    48.4 3224.96   149.2  3187.9
   191.2 3177.86     229 3182.18   300.5 3175.42   313.1 3172.28   325.7 3171.96
   346.9 3168.41   372.3 3167.79   384.5 3169.18   392.9 3166.24   413.6 3154.16
   430.7 3150.63  446.35 3143.83   464.3 3142.51  472.22 3143.83   486.8 3147.72
     498 3152.89   517.3 3155.93   548.4 3167.83   591.7  3181.4     603 3183.66
   611.4 3187.77   670.2 3207.22   840.2 3238.12   899.3 3250.73   967.7  3269.9
#Mann= 3, -1 ,  0
       0     0.1       0  446.35   0.045       0  472.22     0.1       0
Bank Sta=446.35,472.22
XS Rating Curve= 0 ,0
Exp/Cntr(USF)=0,0
Exp/Cntr=0.3,0.1

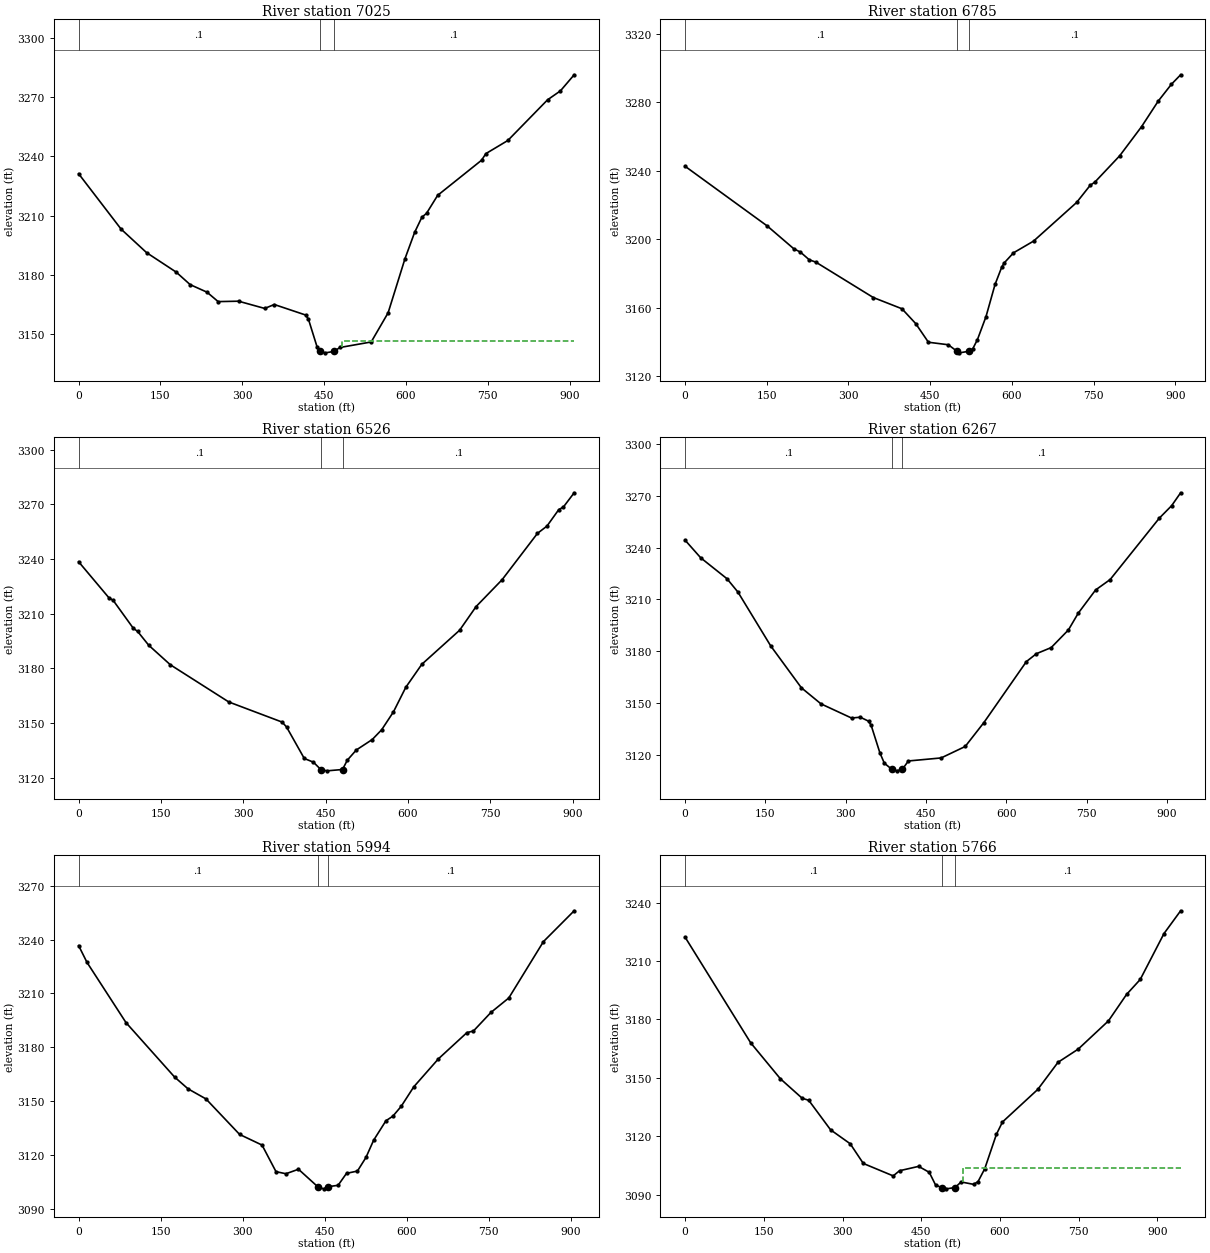
Type RM Length L Ch R = 1 ,7025    ,239.9,239.9,239.9
XS GIS Cut Line= 3
     2201674.912      539564.4022201947.39394125540140.863745225
2201972.09732981540410.335081716
#Sta/Elev= 30
       0 3231.22    77.8 3203.18   124.6 3191.24   178.8 3181.39   204.4 3175.05
   235.3 3171.22   255.7 3166.45   293.1 3166.66     341 3162.99   358.6 3164.98
   416.1 3159.65   421.2 3157.52   437.2 3143.33  441.61 3141.22   452.2  3140.5
   467.2 3141.18   479.2 3143.22   536.2 3146.01   567.2 3160.77   598.1 3188.18
   615.8 3201.52   629.1  3209.2   637.6 3211.16     658 3220.28   738.4 3238.05
   746.4 3241.42   786.6 3248.06   859.4 3268.66     883  3273.2   908.2 3281.35
#Mann= 3, -1 ,  0
       0     0.1       0  441.61   0.045       0   467.2     0.1       0
#XS Ineff= 2 , 0
                          482.97         3146.68
Permanent Ineff=
       F       F
Bank Sta=441.61,467.2
XS Rating Curve= 0 ,0
Exp/Cntr=0.3,0.1

Type RM Length L Ch R = 1 ,6785    ,258.9,258.9,258.9
XS GIS Cut Line= 3
2201568.39561743539564.2363573382201656.61604724540101.435760299
2201757.43939559540452.742114728
#Sta/Elev= 30
       0 3242.66   150.9 3207.78   199.6 3194.48   211.7 3192.54     228 3188.04
   240.1 3186.67   345.5 3166.01   398.2 3159.43   423.4 3150.79   446.8 3139.88
   483.3 3138.41   499.5 3134.55   503.6 3133.69   520.4 3134.56   527.9 3135.87
   536.8 3141.42   552.5 3154.83   569.1 3173.63   581.6 3183.91   586.3 3186.34
     603 3192.11   639.8 3198.95   718.9 3221.52   743.9 3231.58   752.2 3233.35
     798 3248.79   838.1 3265.79   868.7 3280.71     893 3290.58   909.9 3296.11
#Mann= 3, -1 ,  0
       0     0.1       0   499.5   0.045       0   520.4     0.1       0
Bank Sta=499.5,520.4
XS Rating Curve= 0 ,0
Exp/Cntr(USF)=0,0
Exp/Cntr=0.3,0.1

Type RM Length L Ch R = 1 ,6526    ,259.5,259.5,259.5
XS GIS Cut Line= 4
2201327.60167842539614.9785449742201388.76957677540007.587881616
 2201419.4661117540137.8421034682201555.94353674540483.287634921
#Sta/Elev= 30
       0 3238.47    54.9 3218.81      63 3217.27    99.4 3202.07   107.5 3200.25
   127.7 3192.68     167 3181.99   273.5 3161.58   370.6 3150.55   378.7 3147.87
     411  3130.6   427.7 3128.54   441.2 3124.51   452.4 3123.81  480.64 3124.54
   489.4 3129.66   505.8 3135.25   534.8 3140.98     552 3146.35   573.5 3156.19
   595.9 3169.62   625.1 3182.24   693.9 3200.91     724 3213.92   771.3 3228.62
   835.8 3254.07     853 3258.03   874.5 3267.06   883.1 3268.56   902.6 3276.31
#Mann= 3, -1 ,  0
       0     0.1       0   441.2   0.045       0  480.64     0.1       0
Bank Sta=441.2,480.64
XS Rating Curve= 0 ,0
Exp/Cntr=0.3,0.1

Type RM Length L Ch R = 1 ,6267    ,272.6,272.6,272.6
XS GIS Cut Line= 3
2201076.88179419539696.5670020562201180.85587218540210.135932745
2201377.77647444540559.866922356
#Sta/Elev= 30
       0 3244.22    29.2 3234.04    78.2 3221.98    98.6 3214.29   159.8  3183.2
   217.1 3158.99   253.7  3149.7   310.8 3141.51   327.1 3141.99   342.7 3139.67
   347.5 3137.22   363.8 3121.34     372 3115.44   385.8 3111.95   395.7 3111.01
   405.9 3111.99   416.9 3116.71   478.1 3118.46     523 3125.07     558 3138.92
   637.3 3174.12     656 3178.67   683.6  3182.2   715.7 3192.37   734.2 3202.11
   766.5 3215.48   793.7  3221.5   885.5 3256.96   908.5 3264.16   925.3 3271.61
#Mann= 3, -1 ,  0
       0     0.1       0   385.8   0.045       0   405.9     0.1       0
Bank Sta=385.8,405.9
XS Rating Curve= 0 ,0
Exp/Cntr(USF)=0,0
Exp/Cntr=0.3,0.1

Type RM Length L Ch R = 1 ,5994    ,228.1,228.1,228.1
XS GIS Cut Line= 3
2200839.42599706539798.2608365672200918.05056913540142.281573561
 2201185.3966649540626.410193415
#Sta/Elev= 30
       0 3236.62    15.3 3227.29    86.6 3193.78   175.3 3163.53   199.9 3156.96
   232.8 3151.32   294.3 3131.56   335.3 3125.64   360.8 3110.85     379 3109.69
   401.9 3112.19  436.83 3102.55   447.8 3101.29   456.6 3102.52   474.3 3103.25
   489.7  3109.9   509.7 3111.19   525.3 3118.77   539.3 3128.34   561.8 3139.18
   574.4 3141.71   589.6 3147.16   612.7 3158.06   657.8 3173.65   709.8  3188.2
   721.8 3189.13   753.7 3199.43   786.4  3207.5   849.7 3238.85   905.9 3256.01
#Mann= 3, -1 ,  0
       0     0.1       0  436.83   0.045       0   456.6     0.1       0
Bank Sta=436.83,456.6
XS Rating Curve= 0 ,0
Exp/Cntr=0.3,0.1

Type RM Length L Ch R = 1 ,5766    ,107.4,107.4,107.4
XS GIS Cut Line= 4
2200659.56765388 539862.610453882200755.66490779540199.738524946
2200787.17220415540413.9881402032200996.69572495540727.485738998
#Sta/Elev= 30
       0 3222.25     125 3167.99   181.5 3149.55   223.1 3139.53   235.6 3138.48
   277.2 3123.32   314.6 3116.16   339.6 3106.04   396.5 3099.66   408.6 3102.31
     445 3104.55   465.2 3101.49   477.3 3094.96   489.7 3093.57   497.6 3093.01
   514.4 3093.67   525.9 3096.55   549.7 3095.31   558.2 3096.74   570.9  3103.3
   593.2 3121.02   604.7 3127.33     672 3144.07   710.5 3157.98     749 3164.76
   806.7 3179.28   841.2 3192.86   867.2 3200.53   912.5 3224.12   944.2 3235.81
#Mann= 3, -1 ,  0
       0     0.1       0   489.7   0.045       0   514.4     0.1       0
#XS Ineff= 2 , 0
                          529.11         3103.52
Permanent Ineff=
       F       F
Bank Sta=489.7,514.4
XS Rating Curve= 0 ,0
Exp/Cntr(USF)=0,0
Exp/Cntr=0.3,0.1

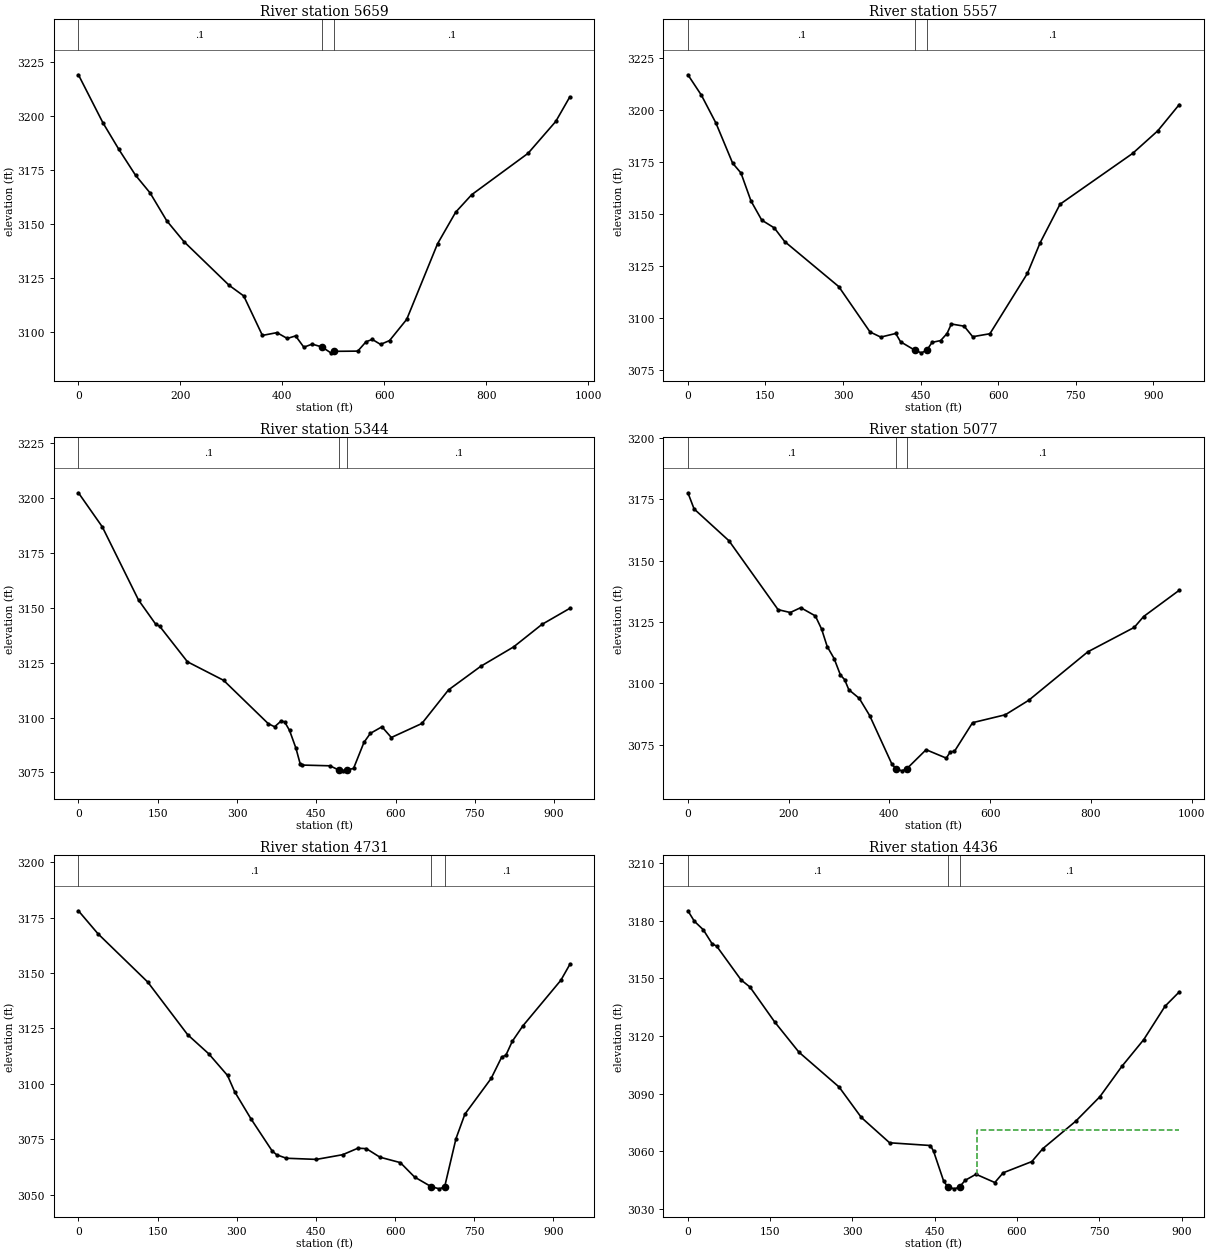
Type RM Length L Ch R = 1 ,5659    ,101.9,101.9,101.9
XS GIS Cut Line= 4
2200631.88642765539871.4037638272200699.03268547 540201.72003215
 2200651.3805025540462.7240343342200866.89833003540752.969148795
#Sta/Elev= 30
       0 3218.99      48 3196.77    79.4 3184.39     112 3172.45   140.6 3164.24
   173.2 3151.36   206.8 3141.73   295.7 3121.42   324.3  3116.5   360.9 3098.22
   389.4  3099.5   409.7  3096.8     426 3097.99   442.2 3092.75   458.5 3094.18
   477.73092.854   495.1 3090.14   501.33090.834     548 3090.94   564.2 3095.28
   576.4 3096.36   592.7 3094.05   610.4 3095.84     644 3105.66   704.4 3140.65
     740 3155.31   771.5 3163.43     882 3182.59   936.4 3197.38   963.9 3208.73
#Mann= 3, -1 ,  0
       0     0.1       0   477.7   0.045       0   501.3     0.1       0
Bank Sta=477.7,501.3
XS Rating Curve= 0 ,0
Exp/Cntr(USF)=0,0
Exp/Cntr=0.3,0.1

Type RM Length L Ch R = 1 ,5557    ,212.5,212.5,212.5
XS GIS Cut Line= 4
2200506.50041681539903.1678583192200543.16031334540245.373703117
2200606.12833515540485.3960309362200816.82411699540774.734948266
#Sta/Elev= 30
       0 3216.82    26.2 3206.98    54.3  3193.6    86.5 3174.42   102.6 3169.71
     122 3156.28   142.8 3147.09     167 3143.37   187.1 3136.82   291.7 3115.21
   352.2 3093.44   372.9 3090.98   401.9 3092.72   411.2 3088.74   439.1 3084.64
   451.5 3083.43  461.77 3084.64   472.2 3088.46   488.7 3089.31   501.1  3092.7
   509.4 3097.26   534.2 3096.22   550.7 3091.17     584 3092.59   656.6 3121.57
   681.1 3136.23   719.6 3154.72   859.9 3179.08   908.7 3189.96   950.2 3202.55
#Mann= 3, -1 ,  0
       0     0.1       0   439.1   0.045       0  461.77     0.1       0
Bank Sta=439.1,461.77
XS Rating Curve= 0 ,0
Exp/Cntr=0.3,0.1

Type RM Length L Ch R = 1 ,5344    ,267.3,267.3,267.3
XS GIS Cut Line= 3
2200322.28204634539928.1456303122200383.72127424540481.098681453
2200547.55921532540816.651387701
#Sta/Elev= 30
       0 3202.19    45.3 3186.65   113.7 3153.43   145.9 3142.54     154 3141.43
   206.3 3125.34   274.7 3116.91   359.2 3097.21   371.3 3095.78   383.4 3098.39
   390.2 3098.03   399.5 3094.12   411.6 3086.03   419.6 3078.95   422.8 3078.38
   475.9 3078.04   492.5 3076.14   500.1 3075.75   508.1 3076.17   520.6 3076.83
   540.3 3088.68   552.4 3092.79   574.3 3095.77   592.1 3090.91   649.9 3097.28
   700.3 3112.56   761.2 3123.26   823.5 3132.11   876.9  3142.3   929.8 3149.63
#Mann= 3, -1 ,  0
       0     0.1       0   492.5   0.045       0   508.1     0.1       0
Bank Sta=492.5,508.1
XS Rating Curve= 0 ,0
Exp/Cntr(USF)=0,0
Exp/Cntr=0.3,0.1

Type RM Length L Ch R = 1 ,5077    ,346.2,346.2,346.2
XS GIS Cut Line= 4
2200224.69597531539945.3689100532200129.15999177540290.314724868
2200139.66281252540498.1564859622200349.01319342540849.997433275
#Sta/Elev= 30
       0 3177.58    12.3 3170.99    81.5 3158.05     179 3130.01   203.2 3128.84
   223.9 3130.82     253 3127.46   265.4 3122.11   276.5 3115.01   290.3 3110.09
   302.8 3103.39   311.1 3101.54   319.4 3097.43   340.2  3093.9   360.8 3086.91
   404.9 3067.18   412.6 3065.32   424.9  3064.4  434.79  3065.3   472.9    3073
     513 3069.57     521 3072.17     529 3072.28   565.1    3084   630.1 3087.22
   676.6 3093.12   793.9 3112.84   886.1 3122.79   904.7 3127.21   975.5 3137.91
#Mann= 3, -1 ,  0
       0     0.1       0   412.6   0.045       0  434.79     0.1       0
Bank Sta=412.6,434.79
XS Rating Curve= 0 ,0
Exp/Cntr=0.3,0.1

Type RM Length L Ch R = 1 ,4731    ,294.7,294.7,294.7
XS GIS Cut Line= 4
2200084.36750741539955.1282331752199887.28936867540360.627137345
2200016.31174727540618.6718945442200023.40088895540810.078719939
#Sta/Elev= 30
       0 3178.13      37 3167.77   131.3 3145.97   206.9 3122.21   246.9 3113.58
   282.5 3103.79   295.8 3096.54   326.9 3084.22   366.8 3069.81   375.6 3067.99
   393.9 3066.44   450.9 3065.92   500.7 3068.04   529.4 3070.96   545.4 3070.78
   571.2 3066.92   609.9 3064.46   636.8 3057.97   668.4  3053.6     684 3052.63
  693.82 3053.56   715.3 3075.31   732.2 3086.36   781.9 3102.46   801.9  3112.1
   809.9 3112.97   821.9 3119.19   841.9 3126.15     914 3146.78   930.9  3153.9
#Mann= 3, -1 ,  0
       0     0.1       0   668.4   0.045       0  693.82     0.1       0
Bank Sta=668.4,693.82
XS Rating Curve= 0 ,0
Exp/Cntr(USF)=0,0
Exp/Cntr=0.3,0.1

Type RM Length L Ch R = 1 ,4436    ,191.9,191.9,191.9
XS GIS Cut Line= 4
     2199930.901      539917.6092199874.87843801540241.643229107
2199705.60426083540476.8588500882199705.29811699540754.066433275
#Sta/Elev= 30
       0 3185.24    11.7  3179.8      28 3175.37    44.2 3168.01    52.3 3166.86
      97  3149.2   113.2 3145.48   157.9 3127.42   202.5 3111.53   275.6 3093.41
   316.2 3077.52   367.7 3064.34   442.2 3062.92   447.9  3059.9   466.3 3044.32
   473.7 3041.37     486 3040.34  495.23 3041.33   505.3 3044.76   525.2 3047.94
   559.5 3043.63   574.7  3048.7     627 3054.55     647 3061.28     707 3075.58
     751 3088.33     791 3104.12     831  3118.1   869.8  3135.5   895.8 3142.97
#Mann= 3, -1 ,  0
       0     0.1       0   473.7   0.045       0  495.23     0.1       0
#XS Ineff= 2 , 0
                           527.8         3070.77
Permanent Ineff=
       F       F
Bank Sta=473.7,495.23
XS Rating Curve= 0 ,0
Exp/Cntr=0.3,0.1