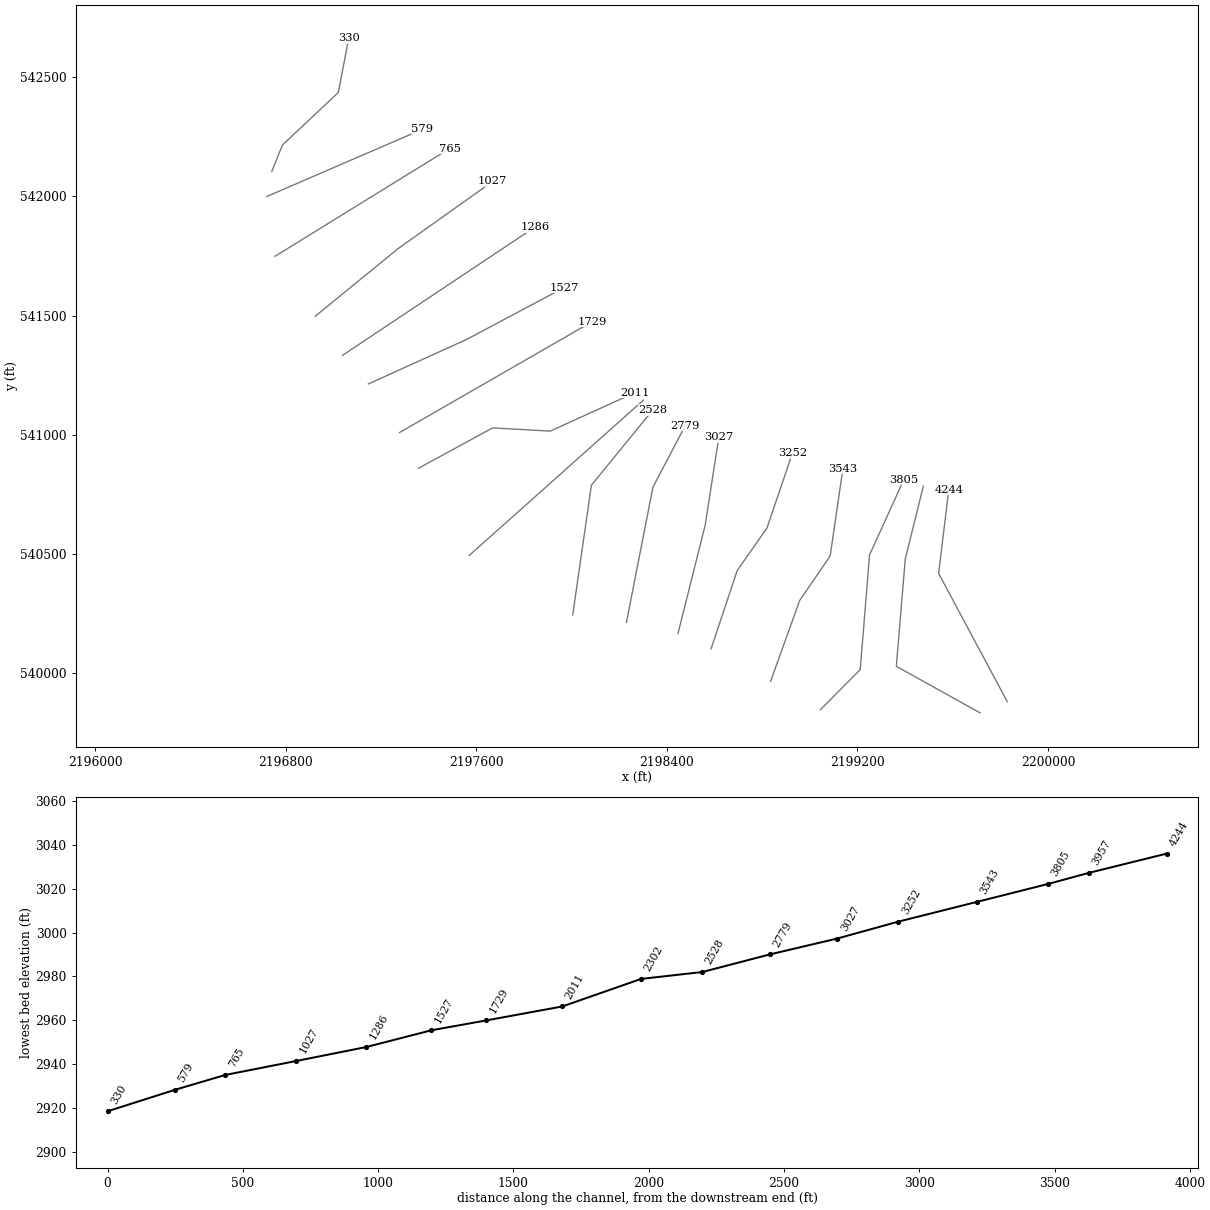
HEC-RAS study BERGOOCK.prj: BERGOOCK

--- BERGOOCK.g01 (geometry) --- (continued)

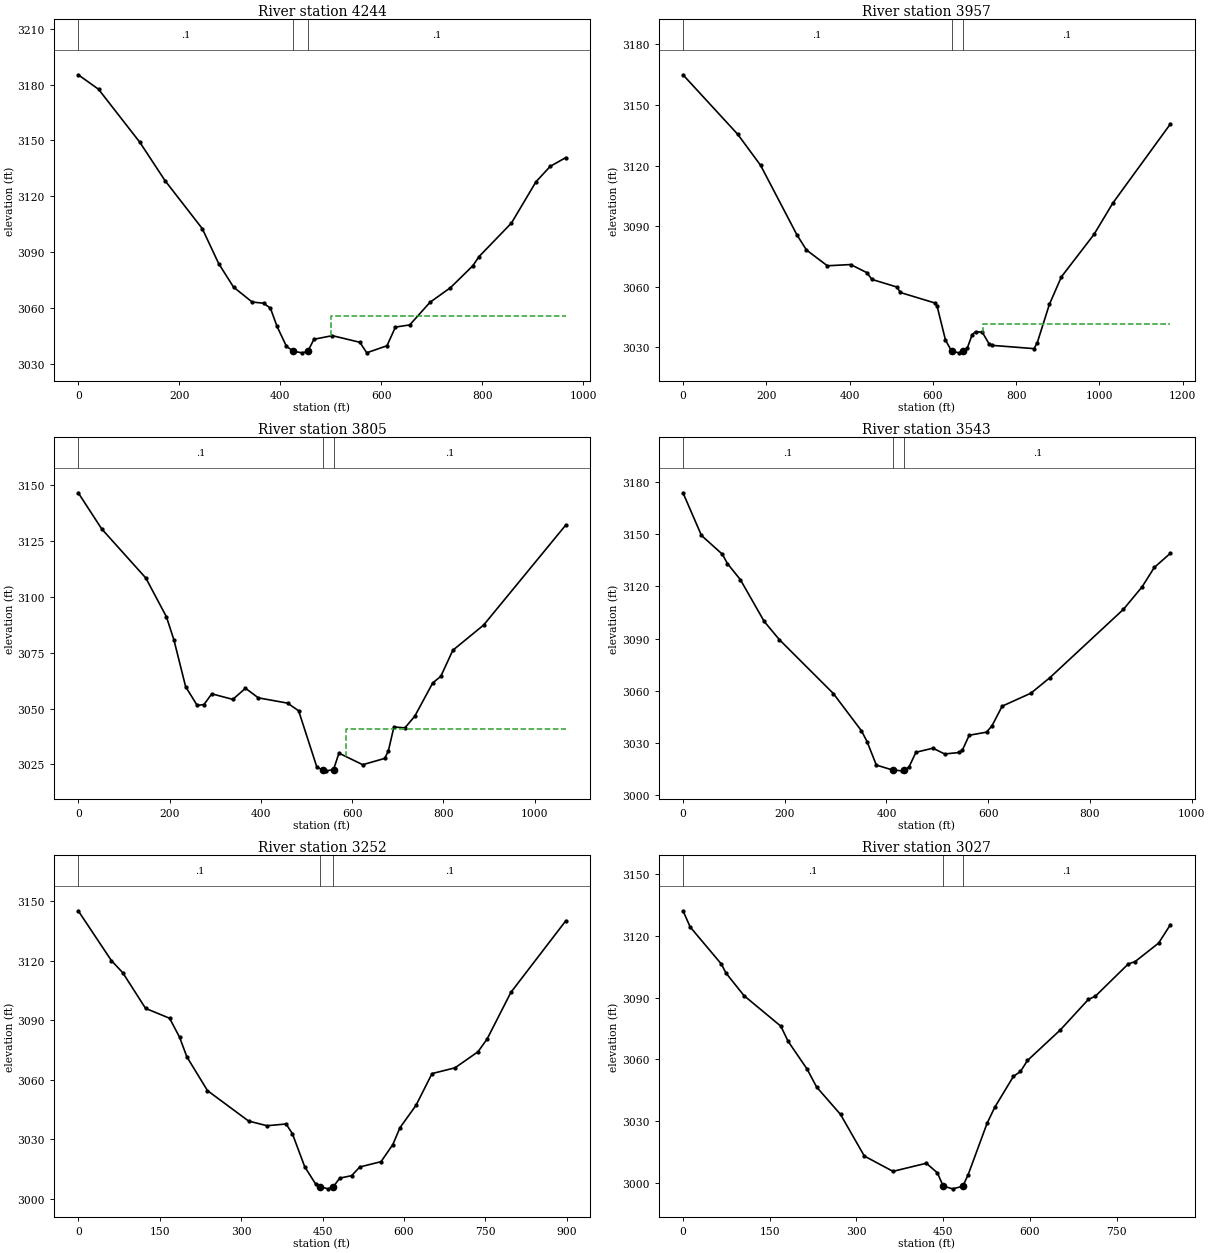
Type RM Length L Ch R = 1 ,4244    ,287.2,287.2,287.2
XS GIS Cut Line= 3
2199829.19285828539877.7339561342199540.90109658540416.508723912
2199583.43594666540767.815078341
#Sta/Elev= 30
       0 3185.25    40.2 3177.49   121.9 3149.04   171.7  3128.5   245.6 3102.67
   278.1 3083.89   307.4 3071.32   344.2 3063.33   366.8 3062.68   380.4 3060.03
   393.4 3050.31   412.2 3039.48   425.9 3036.91     443 3036.06  454.25 3036.84
   466.6 3043.34   502.9 3045.28   557.4 3041.72     571 3036.08   611.1 3039.87
   627.8 3049.88   656.1 3051.04   696.3 3063.19   736.8 3071.03     781 3082.77
     793 3087.62   857.5 3105.72     906 3127.84   934.1 3136.09   964.9 3140.81
#Mann= 3, -1 ,  0
       0     0.1       0   425.9   0.045       0  454.25     0.1       0
#XS Ineff= 2 , 0
                          501.08         3055.68
Permanent Ineff=
       F       F
Bank Sta=425.9,454.25
XS Rating Curve= 0 ,0
Exp/Cntr(USF)=0,0
Exp/Cntr=0.3,0.1

Type RM Length L Ch R = 1 ,3957    ,152.5,152.5,152.5
XS GIS Cut Line= 4
2199715.14297248539830.5707724872199363.19513161540026.404057602
2199400.69362777540476.3725869992199476.70840381540783.504214906
#Sta/Elev= 30
       0    3165   131.6 3135.49   186.4 3120.14   273.5 3085.76   296.4 3078.24
   346.7  3070.4   402.8 3071.01   441.7 3066.97   453.7 3063.65   513.9 3059.87
   521.9 3057.17   606.2 3051.89   610.3 3050.34   630.3 3033.65  644.84 3028.17
   662.4 3027.28     673 3028.13   682.5 3029.53   694.5 3036.32   702.5 3037.71
   718.6 3037.55   734.7 3031.84   742.7 3030.98   843.1 3029.36   850.9  3032.4
   879.8 3051.26   908.7 3064.92     987 3085.93  1032.3 3101.48  1170.7 3140.71
#Mann= 3, -1 ,  0
       0     0.1       0  644.84   0.045       0     673     0.1       0
#XS Ineff= 2 , 0
                          720.42          3041.5
Permanent Ineff=
       F       F
Bank Sta=644.84,673
XS Rating Curve= 0 ,0
Exp/Cntr=0.3,0.1

Type RM Length L Ch R = 1 ,3805    ,261.4,261.4,261.4
XS GIS Cut Line= 4
2199044.55819162539844.0775485052199211.72015246540012.515554853
2199250.68444569540493.9030009532199394.62000784540810.327559666
#Sta/Elev= 30
       0 3146.66    51.4 3130.49   148.1 3108.48   193.2 3091.13   209.6 3080.79
   235.3 3059.82   260.6 3051.45   275.5 3051.85   292.5 3056.64   338.6 3054.15
   366.4 3059.13   394.5 3054.84   458.7 3052.47   482.8 3049.05   522.9 3023.73
   535.4 3022.69     543 3022.16  559.23 3022.69   571.1 3030.09   623.2  3024.9
   671.4 3027.73   679.4 3031.15   691.5  3041.8   715.5  3041.4   737.1 3046.59
   776.6 3061.54   794.2 3064.46   820.5 3076.13   888.1 3087.45  1067.9  3132.2
#Mann= 3, -1 ,  0
       0     0.1       0   535.4   0.045       0  559.23     0.1       0
#XS Ineff= 2 , 0
                          586.77         3040.93
Permanent Ineff=
       F       F
Bank Sta=535.4,559.23
XS Rating Curve= 0 ,0
Exp/Cntr(USF)=0,0
Exp/Cntr=0.3,0.1

Type RM Length L Ch R = 1 ,3543    ,291.1,291.1,291.1
XS GIS Cut Line= 4
2198835.21159788539963.0239513242198957.12031746540302.330906879
 2199085.3916477540489.7565728382199138.97486138540856.627548147
#Sta/Elev= 30
       0 3173.73    36.3 3149.22    77.5 3138.41    87.3 3133.09   112.8 3123.84
   159.6 3099.85   189.3 3089.44   295.6 3058.42   350.8 3037.05   361.9 3030.79
   380.1 3017.34   412.5 3014.46     431 3014.02  435.38 3014.47   443.9 3015.98
     458 3024.69   491.4 3027.03   514.4 3023.71   543.2 3024.56     549 3025.75
   562.7 3034.46   596.7 3036.23   607.4 3039.85   627.5 3051.17   684.1 3058.64
     721 3067.46     866 3106.83   902.4 3119.63   926.6 3130.85   958.4 3139.04
#Mann= 3, -1 ,  0
       0     0.1       0   412.5   0.045       0  435.38     0.1       0
Bank Sta=412.5,435.38
XS Rating Curve= 0 ,0
Exp/Cntr=0.3,0.1

Type RM Length L Ch R = 1 ,3252    ,225.5,225.5,225.5
XS GIS Cut Line= 4
2198585.18181067540099.2866490322198694.92172389540428.506388711
2198819.97418315 540607.152759082198927.16200537 540922.33599823
#Sta/Elev= 30
       0 3145.17      61 3120.09    82.1 3113.92     124 3095.97   168.3 3090.98
   186.6 3081.46   200.2 3071.48   238.1 3054.49   313.8 3039.16   347.8 3036.79
   382.9 3037.69   394.4 3032.82   417.3 3016.04   437.4 3007.37   446.1 3006.01
   460.1 3004.98   469.9 3006.04   481.7 3010.38   503.5 3011.61   518.7    3016
   557.8 3018.68   579.5 3027.31   592.6 3035.78   622.2  3047.1   651.7 3063.09
     694 3065.99   736.2 3074.05   752.9 3080.39     797 3104.05     898 3140.09
#Mann= 3, -1 ,  0
       0     0.1       0   446.1   0.045       0   469.9     0.1       0
Bank Sta=446.1,469.9
XS Rating Curve= 0 ,0
Exp/Cntr(USF)=0,0
Exp/Cntr=0.3,0.1

Type RM Length L Ch R = 1 ,3027    ,248.1,248.1,248.1
XS GIS Cut Line= 3
     2198446.504      540165.017     2198560.084      540617.539
2198618.05549947540989.452315345
#Sta/Elev= 30
       0 3132.11    12.5 3124.23    66.2 3106.32    74.4  3101.9   105.4    3091
   169.3 3076.12   181.6 3068.89   214.6 3055.35   231.1 3046.64   272.4 3033.36
   313.6 3013.18   363.1 3005.76   420.8 3009.69     440 3005.02   449.9 2998.62
   466.2 2997.28   483.8 2998.52   493.1 3004.13   525.9  3029.1   539.1 3036.81
   571.4 3051.81   583.6 3054.19   595.7 3059.52   652.4 3074.31   700.9  3089.1
   713.1  3090.7   769.8 3106.28     782 3107.51   822.4 3116.43     843 3125.44
#Mann= 3, -1 ,  0
       0     0.1       0   449.9   0.045       0   483.8     0.1       0
Bank Sta=449.9,483.8
XS Rating Curve= 0 ,0
Exp/Cntr=0.3,0.1

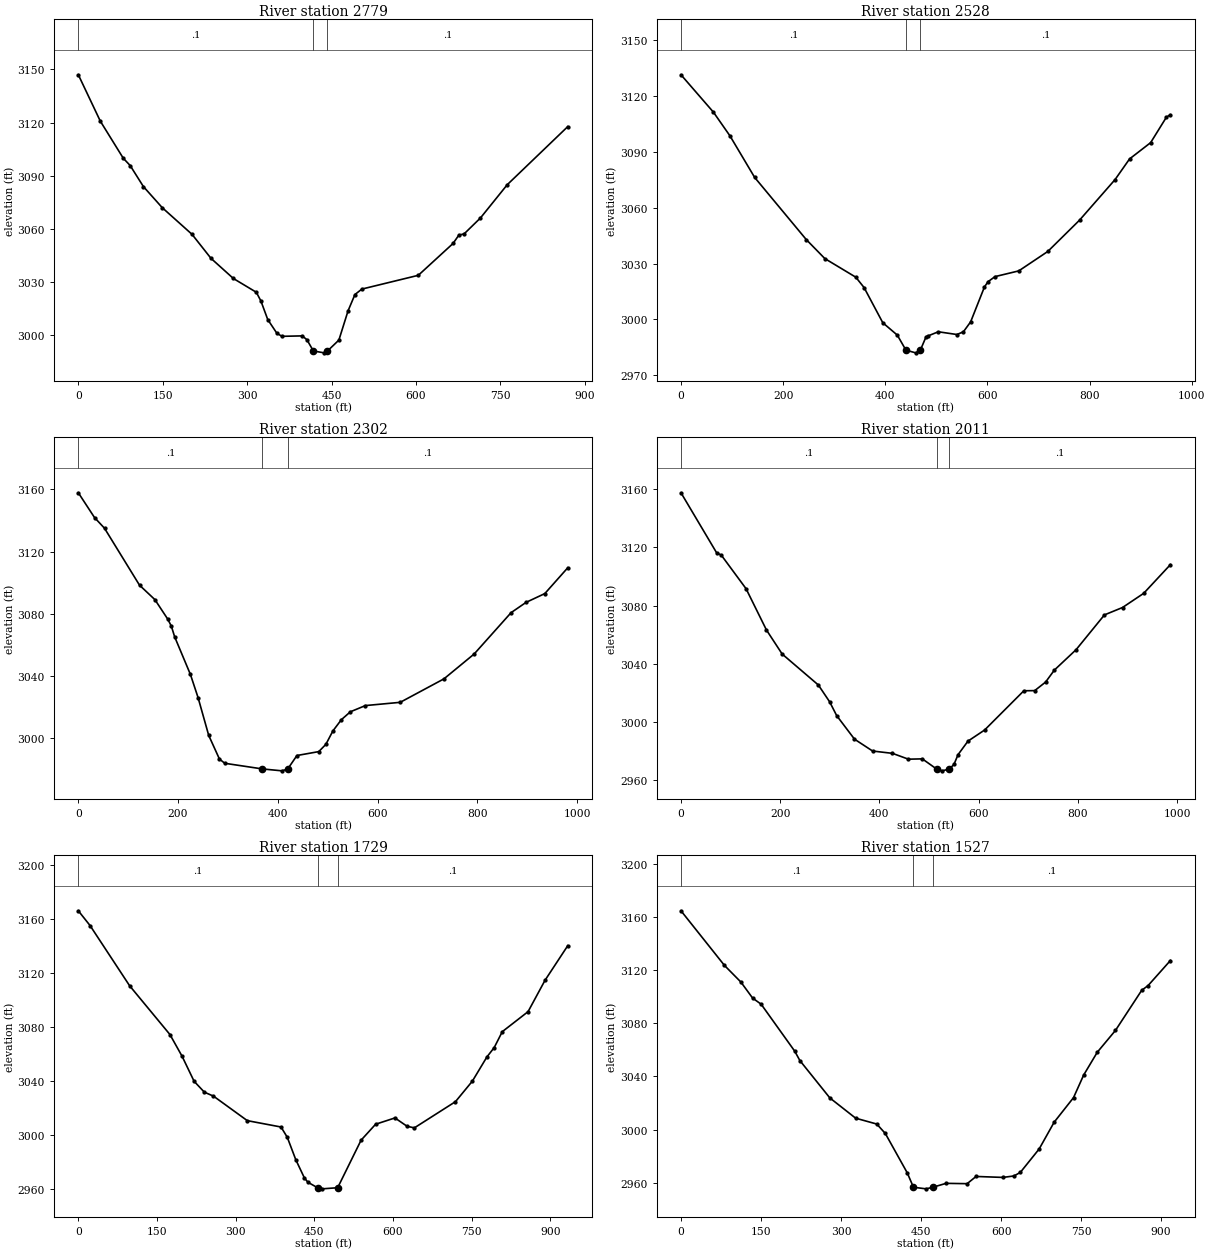
Type RM Length L Ch R = 1 ,2779    ,250.4,250.4,250.4
XS GIS Cut Line= 3
2198229.99388464540210.7871233312198341.00984337540778.627372002
2198476.27066665541036.388563534
#Sta/Elev= 30
       0 3146.98    39.1  3120.8    79.9 3099.86    92.1 3095.77   115.6  3083.9
   149.2 3071.95   202.1 3056.91   235.7 3043.39   275.5 3032.01   316.3 3024.23
   324.4 3019.35   336.6 3008.83   352.9 3001.05   361.9 2999.37   397.8 2999.62
   406.2 2997.46  417.66  2991.1   436.9 2990.05   442.6 2991.05     463 2997.25
   479.3 3013.76   491.5 3022.94   503.8 3026.03   604.1  3033.8   665.8 3051.76
   676.3 3056.54   685.4 3057.15   714.5 3066.15   762.2 3084.95   869.7 3117.73
#Mann= 3, -1 ,  0
       0     0.1       0  417.66   0.045       0   442.6     0.1       0
Bank Sta=417.66,442.6
XS Rating Curve= 0 ,0
Exp/Cntr(USF)=0,0
Exp/Cntr=0.3,0.1

Type RM Length L Ch R = 1 ,2528    ,226.5,226.5,226.5
XS GIS Cut Line= 3
     2198004.293      540242.3662198082.71742955540787.481577593
     2198340.763      541103.127
#Sta/Elev= 30
       0 3131.44    63.5 3111.36    95.8 3098.65   144.3 3076.26   245.3 3042.88
   281.7 3032.65   342.3 3022.65   358.5 3017.09   395.2 2998.16   423.6 2991.52
   440.5 2983.43   459.5 2981.99   468.7  2983.4   479.7 2990.49   483.7 2991.08
   503.9 2993.31   540.3 2991.84     553 2993.29   567.2 2998.64   594.3 3017.43
   601.3 3020.23   614.9 3022.96   661.4 3026.03   718.3 3036.48   780.4 3053.29
   850.1 3075.14   878.4 3086.21   919.7 3094.97   950.7 3108.71   958.4 3109.94
#Mann= 3, -1 ,  0
       0     0.1       0   440.5   0.045       0   468.7     0.1       0
Bank Sta=440.5,468.7
XS Rating Curve= 0 ,0
Exp/Cntr=0.3,0.1

Type RM Length L Ch R = 1 ,2302    ,290.9,290.9,290.9
XS GIS Cut Line= 2
2197569.00231428 540491.517133912198301.45243279541144.852431258
#Sta/Elev= 30
       0 3157.86    32.5  3141.9    52.5 3135.03   122.7 3098.37   153.6 3089.05
   179.1 3076.62   186.5 3072.02   193.2  3065.1   224.8 3040.89   240.1 3026.02
   261.5 3001.63     283 2986.42   293.7 2983.69   369.1 2980.06   408.5 2978.83
   419.9 2980.02   438.4  2988.7   482.2 2991.21   496.4 2995.88   510.5 3004.52
   527.5 3011.76   545.6 3016.86   575.7 3020.85   645.5 3022.94   733.2 3038.05
   793.8 3054.06   867.8 3080.66   897.9  3087.3   935.5 3092.96   981.5 3109.58
#Mann= 3, -1 ,  0
       0     0.1       0   369.1   0.045       0   419.9     0.1       0
Bank Sta=369.1,419.9
XS Rating Curve= 0 ,0
Exp/Cntr(USF)=0,0
Exp/Cntr=0.3,0.1

Type RM Length L Ch R = 1 ,2011    ,282.1,282.1,282.1
XS GIS Cut Line= 4
2197356.96288685540858.634486076 2197667.9274024541027.907192181
2197909.82970123541014.3717741512198265.24159686   541175.903644
#Sta/Elev= 30
       0 3157.57    72.1 3116.13    81.1 3114.75   131.2 3091.57   172.3 3063.17
     204 3046.62   276.9 3025.33   299.7 3013.75   313.9 3004.25   349.8 2988.05
   386.3 2979.89   426.4 2978.29   458.5 2974.28   486.5  2974.5  515.24 2967.54
   526.6 2966.26  541.06 2967.51   550.4 2970.72   558.6 2977.41   578.6 2986.71
   612.1 2994.34   691.2 3021.35   713.1 3021.45   735.1 3027.34   752.7 3035.56
   796.5  3049.6   853.7 3073.55   890.2 3078.64   932.8 3088.38   986.7 3108.14
#Mann= 3, -1 ,  0
       0     0.1       0  515.24   0.045       0  541.06     0.1       0
Bank Sta=515.24,541.06
XS Rating Curve= 0 ,0
Exp/Cntr=0.3,0.1

Type RM Length L Ch R = 1 ,1729    ,202,202,202
XS GIS Cut Line= 2
2197276.78789418541008.3155624762198085.80074285541474.072170937
#Sta/Elev= 30
       0 3165.78    22.4 3154.82    97.9 3110.22   174.7 3074.14   197.8 3058.12
   220.8 3039.52   240.4 3031.44   257.8 3028.51   322.3 3010.36   386.6 3005.65
   398.6 2997.99   414.7 2981.49   431.1    2968   437.8 2964.76   456.2  2960.7
   465.5 2959.86  494.66 2960.69   539.3 2995.89     567  3007.7   603.9 3012.37
     627 3006.19   640.9 3005.01   719.3 3024.41   751.6 3039.64   779.3 3057.54
   793.2 3064.46   808.6 3076.24   857.8 3091.08   890.1 3114.28   933.5 3139.93
#Mann= 3, -1 ,  0
       0     0.1       0   456.2   0.045       0  494.66     0.1       0
Bank Sta=456.2,494.66
XS Rating Curve= 0 ,0
Exp/Cntr(USF)=0,0
Exp/Cntr=0.3,0.1

Type RM Length L Ch R = 1 ,1527    ,240.6,240.6,240.6
XS GIS Cut Line= 3
      2197145.92      541212.488     2197558.906      541399.609
     2197968.531      541617.552
#Sta/Elev= 30
       0 3164.47    81.5 3123.38   112.3 3110.87   134.2 3098.86   150.3 3094.19
   213.3 3058.84   222.8 3051.87   279.1 3023.72   327.4 3008.51     367  3004.1
     383 2997.02   424.1 2967.43  435.73 2956.58   459.4 2955.38     472 2956.57
   496.9 2959.51   536.4 2959.26   553.1 2964.69   603.4 2963.97   624.1 2965.06
   636.1 2967.75   671.4 2985.37   699.5 3005.51   735.8 3023.97   754.8 3040.95
   780.3 3058.09   814.4 3074.51   863.6 3104.67   875.5 3108.21   917.4 3127.08
#Mann= 3, -1 ,  0
       0     0.1       0  435.73   0.045       0     472     0.1       0
Bank Sta=435.73,472
XS Rating Curve= 0 ,0
Exp/Cntr=0.3,0.1

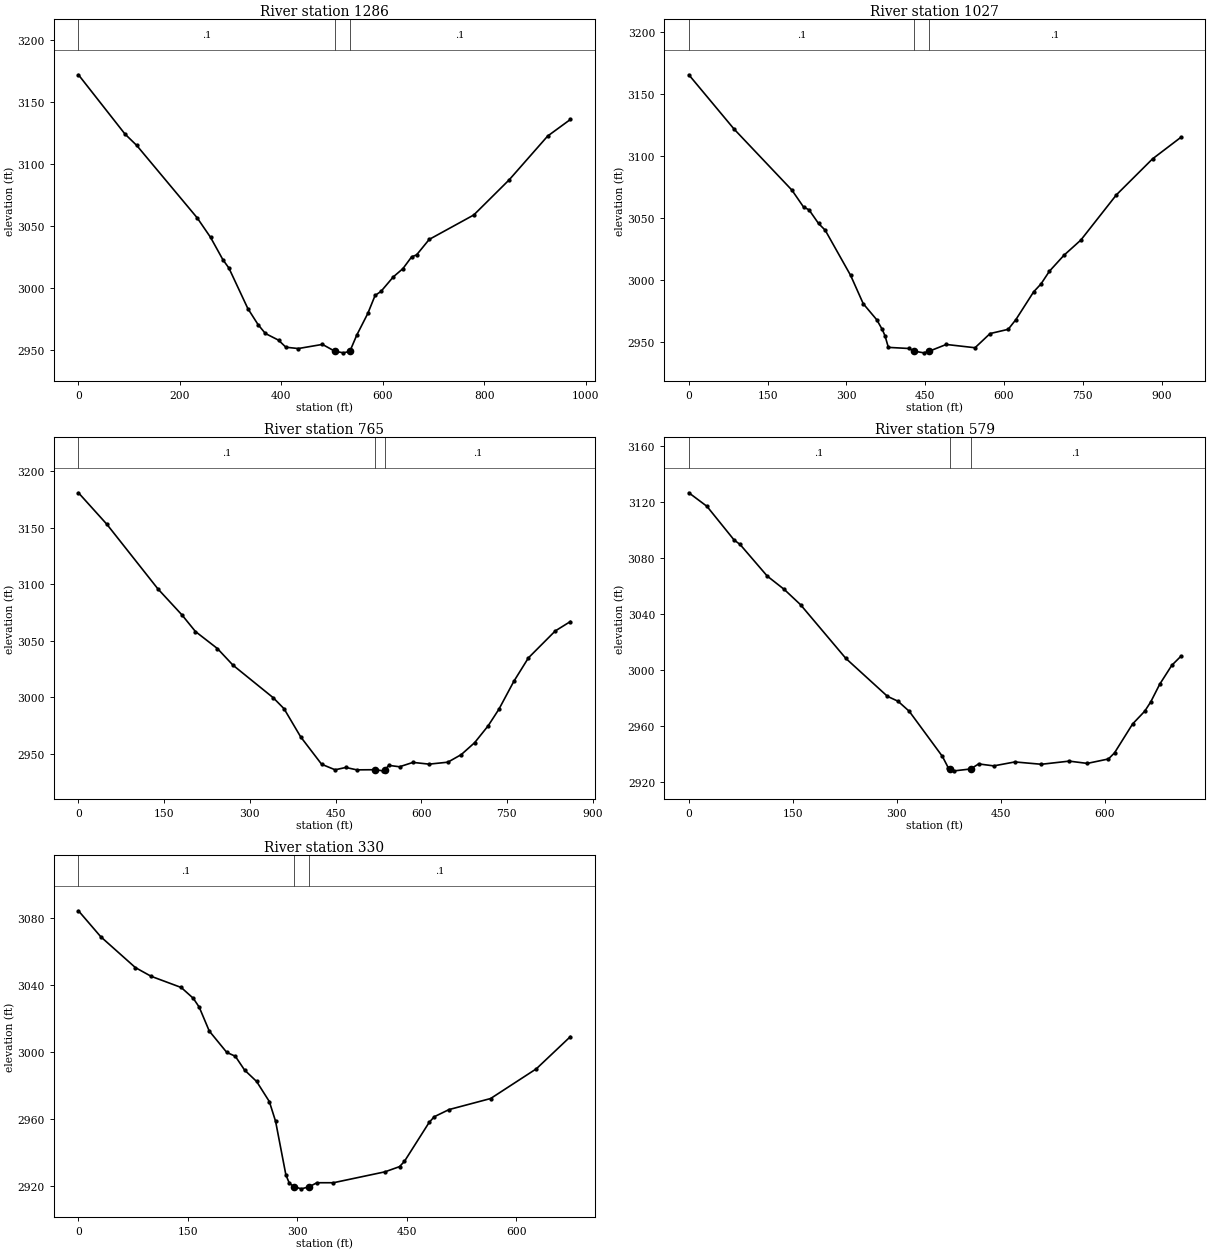
Type RM Length L Ch R = 1 ,1286    ,259.4,259.4,259.4
XS GIS Cut Line= 2
 2197037.4186679541332.7047332332197844.62814285541870.922322256
#Sta/Elev= 30
       0  3171.6    91.7 3123.91   114.8 3114.77   234.1 3056.43   260.4 3040.76
     285 3022.59   296.6 3016.05     334  2983.4   354.2 2970.45   368.6 2963.31
   394.6 2957.92     409 2952.25   433.5 2951.18   481.1 2954.51   505.6 2949.02
   522.5 2947.72  535.23 2948.95   548.8 2961.96   570.6 2979.44     585 2993.95
   596.5 2997.14   620.9 3008.88   639.8 3015.51   657.1 3025.03   666.8 3026.58
   691.7 3039.04   779.6 3058.73   849.5 3087.06   925.3 3122.27   970.2 3135.65
#Mann= 3, -1 ,  0
       0     0.1       0   505.6   0.045       0  535.23     0.1       0
Bank Sta=505.6,535.23
XS Rating Curve= 0 ,0
Exp/Cntr(USF)=0,0
Exp/Cntr=0.3,0.1

Type RM Length L Ch R = 1 ,1027    ,261.8,261.8,261.8
XS GIS Cut Line= 3
     2196922.936      541497.076     2197271.066      541781.151
     2197668.087      542063.466
#Sta/Elev= 30
       0 3165.86    86.2 3121.98   196.3 3072.69   218.4 3059.06   228.8 3056.81
   246.9 3045.79   259.6 3040.35     308 3003.84     332    2981   357.8 2968.01
   368.2 2960.19   373.4 2955.12   379.8 2945.75   418.9 2944.85   428.8  2942.7
   447.3 2941.34  457.79  2942.7     490  2948.1   544.8 2945.46   573.4  2956.9
   607.9 2960.32   622.5 2968.15   656.4 2990.62   670.3 2996.94   686.3 3007.21
     714  3020.1   746.2  3032.4   813.9 3068.93   882.6 3097.93   936.5 3115.32
#Mann= 3, -1 ,  0
       0     0.1       0   428.8   0.045       0  457.79     0.1       0
Bank Sta=428.8,457.79
XS Rating Curve= 0 ,0
Exp/Cntr=0.3,0.1

Type RM Length L Ch R = 1 ,765     ,186.1,186.1,186.1
XS GIS Cut Line= 2
2196753.88195107541748.8352502252197486.79779708542201.217979051
#Sta/Elev= 30
       0 3180.78    49.7 3152.96     139 3095.88   181.3 3072.75   204.8 3058.13
   243.2 3043.11   270.6 3028.35   341.1 2999.54   359.9 2989.89     389 2965.02
   425.7 2940.79   449.3  2935.9   468.1 2937.96   487.3 2935.84   518.5 2935.96
   533.7 2934.97   536.7 2936.01   543.3 2939.81   562.1 2938.57   585.6 2942.43
   613.8 2940.89   646.7 2942.62   670.2 2949.34   693.7 2959.93   717.2 2974.75
     736 2989.38   762.2 3014.09   787.7 3034.82   834.7 3058.63   861.3 3066.98
#Mann= 3, -1 ,  0
       0     0.1       0   518.5   0.045       0   536.7     0.1       0
Bank Sta=518.5,536.7
XS Rating Curve= 0 ,0
Exp/Cntr(USF)=0,0
Exp/Cntr=0.3,0.1

Type RM Length L Ch R = 1 ,579     ,248.8,248.8,248.8
XS GIS Cut Line= 2
 2196720.1972328542000.2976785532197372.11270183542281.925445711
#Sta/Elev= 30
       0 3126.36    26.1 3116.73    65.3 3092.74      74  3089.5   113.2 3066.98
   137.6 3057.53   161.2 3046.61   226.6 3008.33   286.7 2981.28   301.9 2977.81
   318.1 2970.65     366 2938.47   374.7 2930.15  376.51 2929.52   383.4 2928.19
  406.77 2929.52   418.3 2933.12   440.1 2931.72   470.6 2934.53   508.8 2932.87
     549 2935.11   575.1 2933.49   605.6 2936.65   614.4 2940.99   640.5 2961.59
     658 2970.69   666.6 2977.24   679.7 2989.96   697.1 3003.41   710.1 3009.79
#Mann= 3, -1 ,  0
       0     0.1       0  376.51   0.045       0  406.77     0.1       0
Bank Sta=376.51,406.77
XS Rating Curve= 0 ,0
Exp/Cntr(USF)=0,0
Exp/Cntr=0.3,0.1

Type RM Length L Ch R = 1 ,330     ,,,
XS GIS Cut Line= 4
2196740.39769688542104.7920651372196785.30872944542216.521951032
2197019.72241161542436.6955497082197063.53805314 542664.53688565
#Sta/Elev= 30
       0 3084.22    30.6 3068.72      78 3050.34    99.6 3045.14   140.8 3038.47
   157.3 3032.03   165.4 3026.79   179.2 3012.52   203.2 2999.76   214.9 2997.47
   227.6 2989.23   244.1 2982.42   261.5 2970.45   270.1 2958.62   284.2 2926.68
     289 2921.65   295.5 2919.66   305.4 2918.39  316.13 2919.64   326.7 2922.03
   349.3 2922.03     420 2928.54   439.9 2931.64   446.6 2934.78   480.4 2957.96
   487.4 2961.38   507.7 2965.66   564.7 2972.25   627.3 2989.97674.0339  3009.2
#Mann= 3, -1 ,  0
       0     0.1       0   295.5   0.045       0  316.13     0.1       0
Bank Sta=295.5,316.13
XS Rating Curve= 0 ,0
Exp/Cntr(USF)=0,0
Exp/Cntr=0.3,0.1
LCMann Table=0

Chan Stop Cuts=-1
Use User Specified Reach Order=0
Composite Channel Slope=5